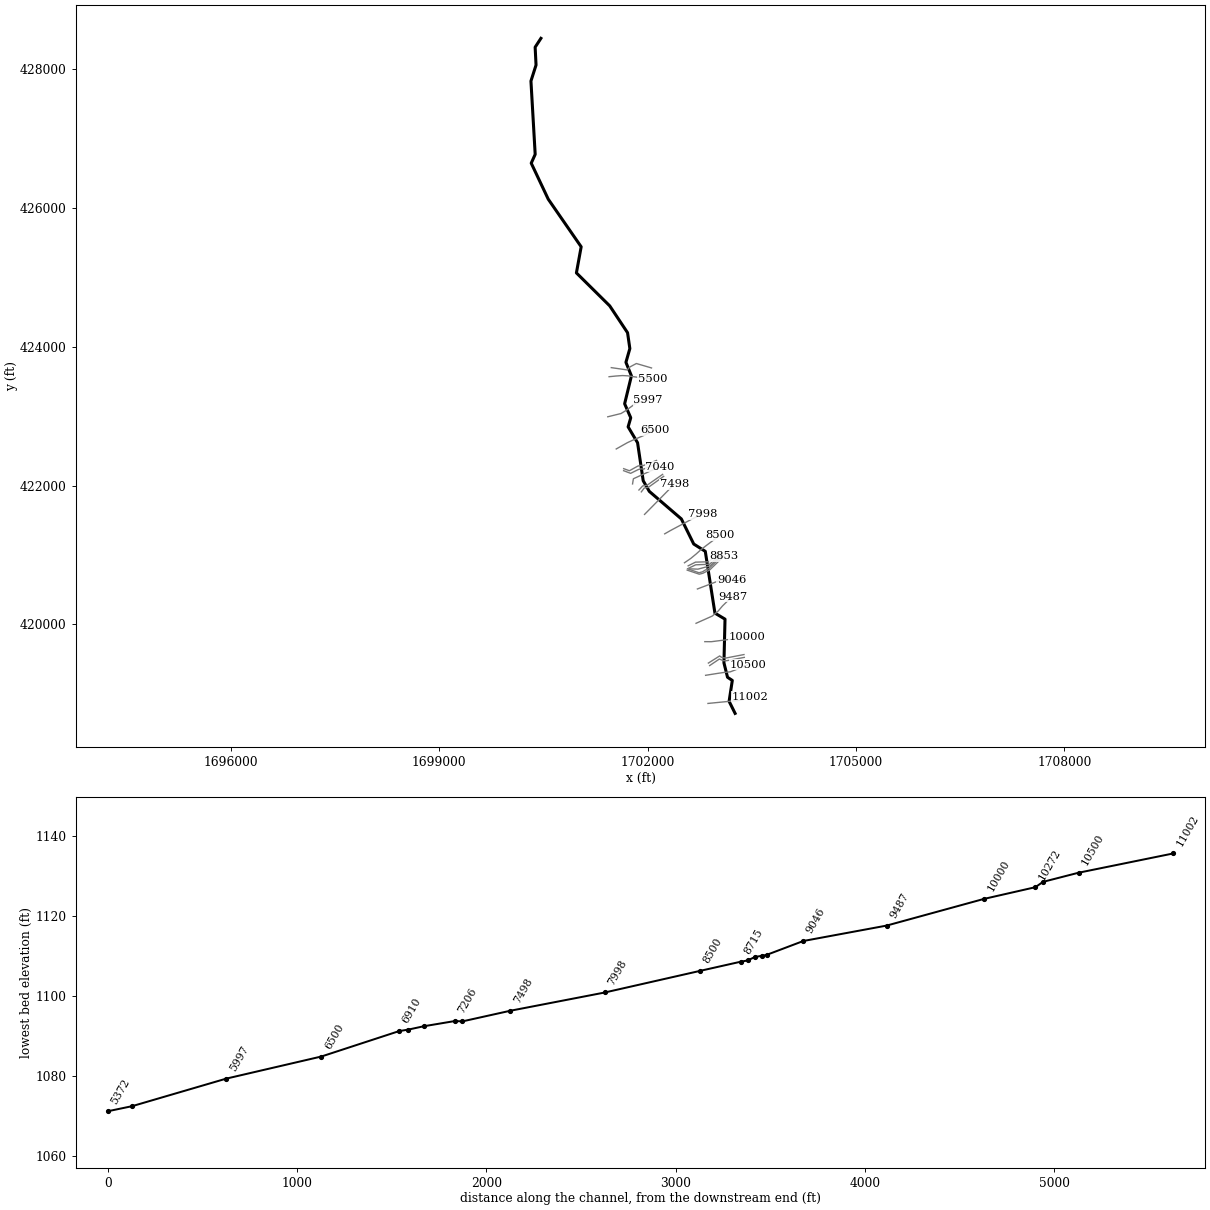
--- RUSHRN2.prj (project) ---

Proj Title=RUSHRN2
Current Plan=p01
Default Exp/Contr=0,0
English Units
Geom File=g01
Flow File=f01
Plan File=p01
BEGIN DESCRIPTION:
---------- MODELED AS PART OF WVEMD CTP PROGRAM, 2023----------
Stream Name: Rush Run II
Flood Zone:  AFH
Wetzel County, WV
HEC-RAS Version: RAS 6.3
Vertical Datum: NAVD88
Projection: NAD 1983 StatePlane West Virginia S FIPS 4702 (US Feet)
Terrain: 1-meter West Virginia FEMA R3 South Central (collected 2018-2020)
Land Use: 2019 NLCD
Hydrologic Method:
WV SIR2010-5033 regression equations
Additional Model Notes:
None
END DESCRIPTION:
DSS Export Rating Curves= 0
DSS Export Rating Curve Sorted= 0
DSS Export Volume Flow Curves= 0
DXF OffsetX= 0
DXF OffsetY= 0
DXF ScaleX= 0
DXF ScaleY= 0

--- RUSHRN2.p01 (plan) ---

Plan Title=Floodplain
Program Version=6.30
Short Identifier=Floodplain
Geom File=g01
Flow File=f01
Subcritical Flow
K Sum by GR= 0
Std Step Tol= 0.01
Critical Tol= 0.01
Num of Std Step Trials= 20
Max Error Tol= 0.3
Flow Tol Ratio= 0.001
Split Flow NTrial= 30
Split Flow Tol= 0.02
Split Flow Ratio= 0.02
Log Output Level= 0
Friction Slope Method= 1
Unsteady Friction Slope Method= 2
Unsteady Bridges Friction Slope Method= 1
Parabolic Critical Depth
Global Vel Dist= 0 , 0 , 0
Global Log Level= 0
CheckData=True
Encroach Param=-1 ,0,0, 0
Mapping Interval=1HOUR
Computation Time Step Use Courant=        0
Computation Time Step Use Time Series=    0
Computation Time Step Count To Double=0
Computation Time Step Max Doubling=0
Computation Time Step Max Halving=0
Computation Time Step Residence Courant=0
Run HTab= 0
Run UNet= 0
Run Sediment= 0
Run PostProcess= 0
Run WQNet= 0
Run RASMapper= 0
UNET Theta= 0
UNET Theta Warmup= 0
UNET ZTol= 0
UNET ZSATol= 0
UNET MxIter= 0
UNET Max Iter WO Improvement= 0
UNET MaxInSteps= 0
UNET DtIC= 0
UNET DtMin= 0
UNET MaxCRTS= 0
UNET WFStab= 0
UNET SFStab= 0
UNET WFX= 1
UNET SFX= 1
UNET Gravity=32.17405
UNET 1D Methodology=Finite Difference
UNET DSS MLevel= 1
UNET Pardiso=0
UNET DZMax Abort= 0
UNET Use Existing IB Tables= 0
UNET Froude Reduction=False
UNET Froude Limit= 0
UNET Froude Power= 0
UNET D1 Cores= 0
UNET WindReference=Eulerian
UNET WindDragFormulation=Hsu (1988)
UNET D2 Coriolis=0
UNET D2 Cores= 0
UNET D2 Theta= 1
UNET D2 Theta Warmup= 1
UNET D2 Z Tol= 0.01
UNET D2 Volume Tol= 0.01
UNET D2 Max Iterations= 20
UNET D2 Equation= 0
UNET D2 RampUpFraction=0.1
UNET D2 TimeSlices= 1
UNET D2 Turbulence Formulation=Non-Conservative (original)
UNET D2 Eddy Viscosity=0.3
UNET D2 Transverse Eddy Viscosity=0.1
UNET D2 Smagorinsky Mixing=0
UNET D2 BCVolumeCheck=0
UNET D2 Cores=0
UNET D2 SolverType=PARDISO (Direct)
UNET D2 Minimum Iterations= 3
UNET D2 Maximum Iterations= 30
UNET D2 Restart Number= 10
UNET D2 Relaxation Coeff=1.3
UNET D2 SOR Precondition Iterations= 10
UNET D2 ILUT Maximum Fill= 8
UNET D2 ILUT Tolerance=1E-08
UNET D2 Convergence Tolerance=0.00001
UNET D1D2 MaxIter= 0
UNET D1D2 ZTol=0.01
UNET D1D2 QTol=0.1
UNET D1D2 MinQTol=1
Write IC File= 0
Write IC File at Fixed DateTime=0
Write IC File at Sim End=0
Echo Input=False
Echo Parameters=False
Echo Output=False
Write Detailed= 0
HDF Write Warmup=0
HDF Write Time Slices=0
HDF Flush=0
HDF Compression= 1
HDF Chunk Size= 1
HDF Spatial Parts= 1
HDF Use Max Rows=0
HDF Fixed Rows= 1
Calibration Method= 0
Calibration Iterations= 20
Calibration Max Change=0.05
Calibration Tolerance=0.2
Calibration Maximum=1.5
Calibration Minimum=0.5
Calibration Optimization Method= 1
WQ AD Non Conservative
WQ ULTIMATE=-1
WQ Max Comp Step=1HOUR
WQ Output Interval=15MIN
WQ Output Selected Increments= 0
WQ Output face flow=0
WQ Output face velocity=0
WQ Output face area=0
WQ Output face dispersion=0
WQ Output cell volume=0
WQ Output cell surface area=0
WQ Output cell continuity=0
WQ Output cumulative cell continuity=0
WQ Output face conc=0
WQ Output face dconc_dx=0
WQ Output face courant=0
WQ Output face peclet=0
WQ Output face adv mass=0
WQ Output face disp mass=0
WQ Output cell mass=0
WQ Output cell source sink temp=0
WQ Output nsm pathways=0
WQ Output nsm derived pathways=0
WQ Create Restart=0
WQ Fixed Restart=0
WQ System Summary=0
WQ Write To DSS=0
Sorting and Armoring Iterations= 10
XS Update Threshold= 0.02
Bed Roughness Predictor= 0
Hydraulics Update Threshold= 0.02
Energy Slope Method= 1
Volume Change Method= 1
Sediment Retention Method= 0
Sediment TS Multiplier= 1
Warm Up Method= 0
XS Weighting Method= 0
Number of US Weighted Cross Sections= 1
Number of DS Weighted Cross Sections= 1
Upstream XS Weight=0
Main XS Weight=1
Downstream XS Weight=0
Number of DS XS's Weighted with US Boundary= 1
Upstream Boundary Weight= 1
Weight of XSs Associated with US Boundary= 0
Number of US XS's Weighted with DS Boundary= 1
Downstream Boundary Weight= 0.5
Weight of XSs Associated with DS Boundary= 0.5
Percentile Method= 0
Sediment Output Level= 3
Mass or Volume Output= 0
Output Increment Type= 1
Profile and TS Output Increment= 1
Transport Output Increment 1
XS Output Flag= 0
XS Output Increment= 10
Read HDF5 Sediment Hotstart= 0
Sediment Hotstart Type= 0
Write Gradation File= 0
Read Gradation Hotstart= 0
Write HDF5 File= 1
Write Binary Output= 1
Write DSS Sediment File= 0
DSS Sediment Output Type= 1
SV Curve= 0
Specific Gage Flag= 0
Subcell Erosion Methods= 0
Subcell Deposition Methods= 0
Advection Scheme= 1
Matrix Solver= 0
Implicit Weighting Factor= 1
Maximum Outer Loop Convergence Iterations= 5
Convergence Maximum Absolute= 0.001
Convergence RMSE= 0.0001
Grain Fractions Max Abs Error= 0.001
Max Subgrid Regions= 1
Max Subgrid Length Scale= 3.402823E+38
Initial Layer Thickness= 3.402823E+38
Min Layer Thickness= 3.402823E+38
Max Layer Thickness= 3.402823E+38
Number of Layers= 5

--- RUSHRN2.f01 (steady flow) ---

Flow Title=Flow
Program Version=4.00
Number of Profiles=1
Profile Names=F01pct
River Rch & RM=RUSHRN2,Main,11002
     722
River Rch & RM=RUSHRN2,Main,7040
     843
River Rch & RM=RUSHRN2,Main,5997
     977
River Rch & RM=RUSHRN2,Main,3192
    1140
Boundary for River Rch & Prof#=RUSHRN2,Main      ,1
Up Type=0
Dn Type=3
Dn Slope=0.004284

--- RUSHRN2.g01 (geometry) ---

Geom Title=Geometry
Program Version=6.31

River Reach=RUSHRN2         ,Main
Reach XY= 30
1703260.70360982418718.002154416     1703174.403      418891.333
     1703220.377      419192.488     1703151.675      419237.945
     1703100.019      419445.603     1703115.515       420075.29
     1702970.362      420162.072     1702831.407      421052.106
     1702665.075      421157.484     1702486.861      421519.077
     1702026.089      421915.279     1701937.757      422069.214
     1701856.658      422616.251     1701720.802      422845.087
     1701758.575      422975.906     1701670.599      423177.688
     1701768.261      423579.636     1701689.163      423774.961
     1701745.661      423972.707     1701712.537      424201.059
     1701455.807      424587.962     1700976.438      425062.682
     1701044.852      425438.924     1700571.104      426124.585
      1700326.13      426643.295     1700382.993      426770.245
     1700321.956       427826.28     1700395.308      428056.666
     1700382.394      428313.914     1700465.415      428441.413

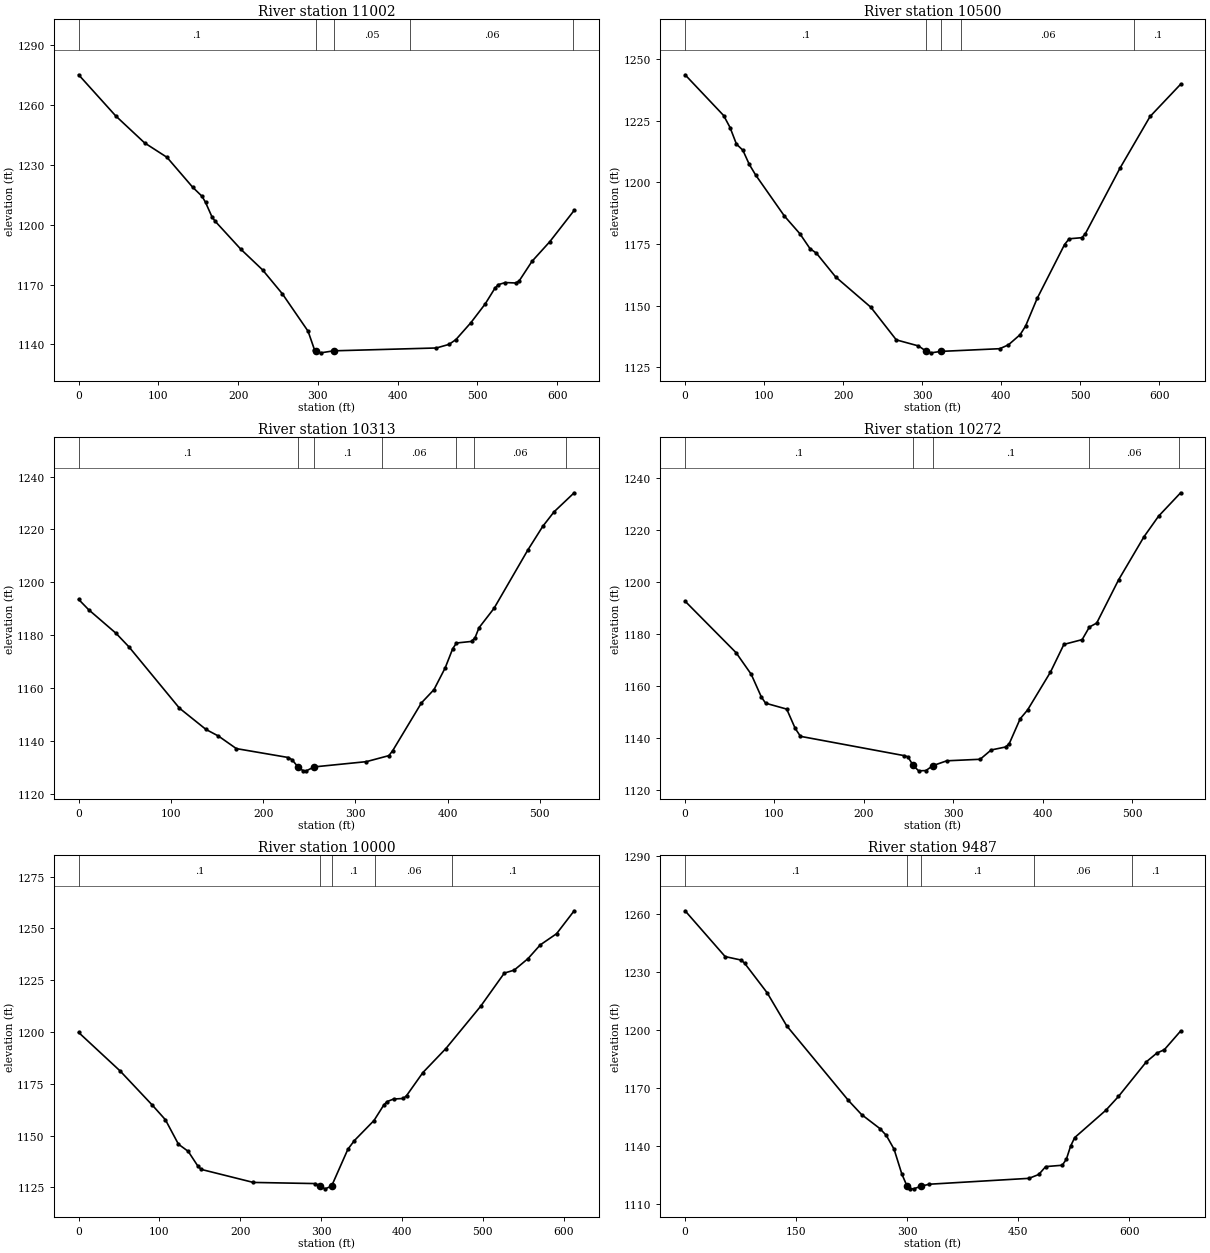
Type RM Length L Ch R = 1 ,11002   ,497,501.6,494.4
XS GIS Cut Line= 6
1702869.81492859418861.0940062551703124.69794901418886.197958678
  1703224.264679  418895.67366151703299.02601242 418902.42069526
 1703385.8135685418919.6880491671703480.70248634418956.340206832
#Sta/Elev= 30
       0 1275.29    46.5 1254.65    82.7 1241.11   110.8 1233.86     143 1218.86
   154.8 1214.28   159.1 1211.27   167.1 1204.08   171.1 1201.83   203.3 1187.77
   230.6 1177.39   255.5 1165.34   287.7 1146.59   295.7 1137.35   297.3 1136.77
   303.7 1135.73   319.8 1136.74   448.6 1138.17   464.5 1139.98   473.1 1142.38
   491.8 1150.83   509.8 1160.26     522 1168.16   526.4 1169.97     535 1171.01
   547.9 1170.79   552.2 1171.69   568.5 1181.65   590.8  1191.5   621.4 1207.23
#Mann= 5 ,-1,0
       0      .1       0   297.3    .045       0   319.8     .05       0
  416.13     .06       0  619.69      .1       0
Bank Sta=297.3,319.8
XS Rating Curve= 0 ,0
Exp/Cntr(USF)=0,0
Exp/Cntr=0.3,0.1

Type RM Length L Ch R = 1 ,10500   ,185.9,187.5,181.8
BEGIN DESCRIPTION:
Structure 11 XS 4
END DESCRIPTION:
XS GIS Cut Line= 6
1702835.96230601419266.4081562611703017.13648434419295.185001582
1703092.41258051 419306.363456921703192.05411351419316.452347502
1703263.34301293419343.9608226721703439.89154434 419417.10601759
#Sta/Elev= 30
       0 1243.67    48.8 1227.14    56.9 1222.28      65 1215.55    73.1 1213.08
    81.2 1207.35    89.3 1203.02   125.7 1186.38   145.3  1179.2   158.1 1173.16
   166.2 1171.32   190.5  1161.7     235 1149.42   267.3 1136.16   295.4  1133.7
  305.431131.495   311.5  1130.9   323.3 1131.48   398.3 1132.58   409.3 1134.15
   424.1 1138.29     431  1141.8   445.6 1152.98   480.3 1174.83   486.1 1177.15
     502  1177.6   506.3 1179.02   550.3 1205.72   588.5 1226.75   627.2 1239.84
#Mann= 5 ,-1,0
       0      .1       0  305.43    .045       0   323.3      .1       0
  349.55     .06       0  568.48      .1       0
Bank Sta=305.43,323.3
XS Rating Curve= 0 ,0
Exp/Cntr(USF)=0,0
Exp/Cntr=0.3,0.1

Type RM Length L Ch R = 1 ,10313   ,41.9,40.8,40
BEGIN DESCRIPTION:
Structure 11 XS 3
END DESCRIPTION:
XS GIS Cut Line= 6
 1702894.4091552 419406.48674738 1703034.6930286419500.993777886
1703073.08650975419484.0120458421703090.06824179419477.367020259
1703139.53676557419476.6286840841703393.52441006419524.620535512
#Sta/Elev= 30
       0 1193.53    10.8 1189.65    40.6 1180.68    54.6 1175.54   109.3 1152.35
   138.1 1144.29   151.6 1141.79     171 1137.04   227.3 1133.67   231.4 1132.84
  237.711130.145   243.4 1128.65   246.8 1128.62   255.4 1130.11     312  1132.1
   336.4 1134.38   340.5 1136.24   371.7 1154.35   385.3 1159.37   397.5 1167.65
   405.6 1174.87   409.7 1177.02     426 1177.62   429.9 1179.08   434.1 1182.79
   450.4 1190.15     487  1212.2   503.3 1221.22   515.5 1226.69   537.3  1233.9
#Mann= 7 ,-1,0
       0      .1       0  237.71    .045       0   255.4      .1       0
  328.84     .06       0  408.84      .1       0  428.84     .06       0
  528.84      .1       0
Bank Sta=237.71,255.4
XS Rating Curve= 0 ,0
Exp/Cntr(USF)=0,0
Exp/Cntr=0.3,0.1

Type RM Length L Ch R = 1 ,10272   ,269.8,272,272.1
BEGIN DESCRIPTION:
Structure 11 XS 2
END DESCRIPTION:
XS GIS Cut Line= 6
 1702875.9507508419442.6652199951703038.38470948419545.293948436
1703058.31978623419530.5272249191703078.25486298419520.190518457
1703130.67673146419515.7605014021703388.35605682419565.229025183
#Sta/Elev= 30
       0 1192.69      57 1172.85      74 1164.49    85.4 1155.69    90.1 1153.36
   113.7 1151.08   123.2 1143.62   129.1 1140.58   245.3 1133.13   249.3 1132.68
  255.091129.376   261.3 1127.28   269.4 1127.39   277.4 1129.31   292.8 1131.15
   330.1 1131.74   342.4 1135.32   358.6 1136.48   362.7  1137.8   374.9 1147.36
   383.1 1150.72   408.8 1165.37   423.8 1176.03   444.2 1177.87   452.3 1182.72
   460.5 1184.26   484.9 1200.87   513.4 1217.54   529.7 1225.47   554.4 1234.49
#Mann= 5 ,-1,0
       0      .1       0  255.09    .045       0   277.4      .1       0
  452.01     .06       0  552.01      .1       0
Bank Sta=255.09,277.4
XS Rating Curve= 0 ,0
Exp/Cntr(USF)=0,0
Exp/Cntr=0.3,0.1

Type RM Length L Ch R = 1 ,10000   ,505.7,513.6,515.4
BEGIN DESCRIPTION:
Structure 11 XS 1
END DESCRIPTION:
XS GIS Cut Line= 6
 1702824.8563571419751.1033810821702919.34206051419750.479694679
1703179.71063426419783.8625019191703254.10188967419793.398900166
1703340.89141425419804.5278149251703433.78492926419817.193472013
#Sta/Elev= 30
       0  1199.8    51.3 1181.24    91.3 1164.69   107.4 1157.67   123.5 1145.89
   135.6 1142.43   147.7 1135.24   151.7 1133.73   216.2 1127.44   292.9 1126.89
  299.021125.688     305 1124.35     313 1125.66   333.2 1143.47   341.3 1147.67
   365.5 1157.32   377.6 1164.78   381.6 1166.43   389.7 1167.68   401.8 1167.95
   405.8 1169.32     426 1180.45   454.5 1192.06   497.4  1212.4   526.8 1228.46
   538.9 1229.86     556  1235.4   571.2 1242.04   591.4 1247.44   613.2 1258.51
#Mann= 5 ,-1,0
       0      .1       0  299.02    .045       0     313      .1       0
  366.99     .06       0  461.99      .1       0
Bank Sta=299.02,313
XS Rating Curve= 0 ,0
Exp/Cntr(USF)=0,0
Exp/Cntr=0.3,0.1

Type RM Length L Ch R = 1 ,9487    ,443.2,440.1,436.4
XS GIS Cut Line= 6
1702698.49702975420015.4220781771702932.47392401420120.142341167
1703017.85597108420193.0637832581703078.10519442420264.014756843
1703150.75596775420335.4089710121703233.26006784420401.477736503
#Sta/Elev= 30
       0  1261.5    54.1 1237.81    75.9 1235.99    80.3 1234.41   110.9 1219.05
   137.1 1202.07   220.6  1163.4   238.3 1156.13   263.1 1148.86   271.7 1145.35
   282.2 1138.24   292.7  1125.4  299.841119.042   303.2 1117.86   308.5 1117.69
   318.6    1119   329.5 1120.07   464.5 1123.12   477.7 1125.12     487 1129.19
   509.4 1129.89     515 1133.05   520.6  1139.7   526.2 1144.19   568.2  1158.3
   585.3 1165.45     623 1183.39   637.1 1187.88   647.3 1189.66   669.3 1199.32
#Mann= 5 ,-1,0
       0      .1       0  299.84    .045       0   318.6      .1       0
  471.72     .06       0  603.58      .1       0
Bank Sta=299.84,318.6
XS Rating Curve= 0 ,0
Exp/Cntr(USF)=0,0
Exp/Cntr=0.3,0.1

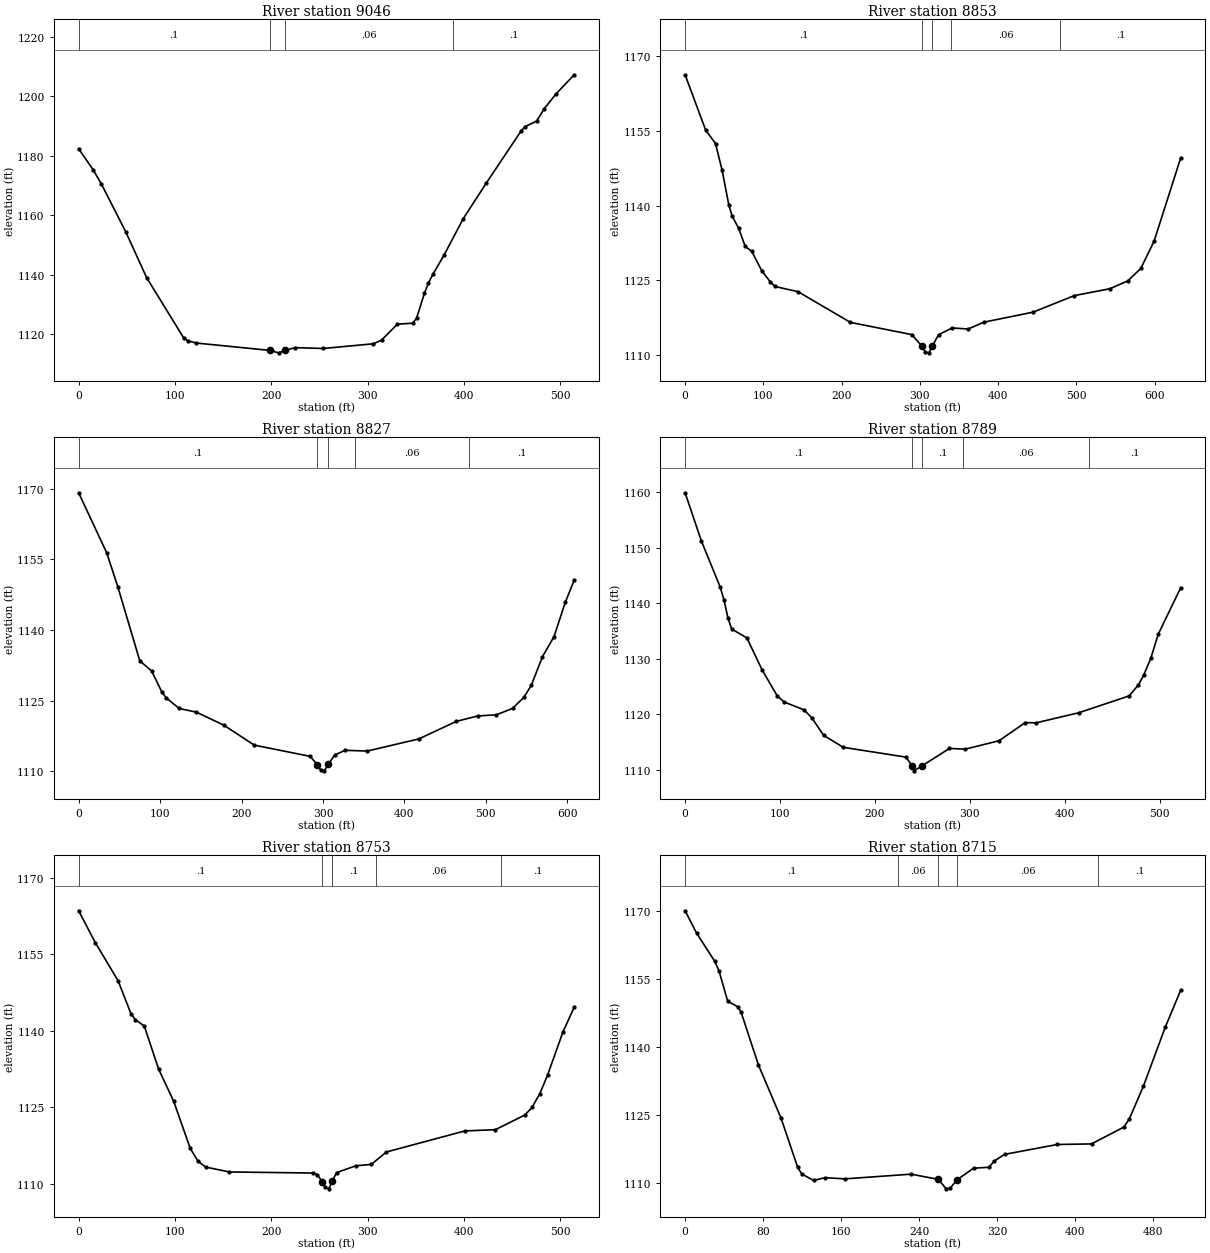
Type RM Length L Ch R = 1 ,9046    ,193.1,193.9,193.3
BEGIN DESCRIPTION:
Structure 10 XS 4
END DESCRIPTION:
XS GIS Cut Line= 3
1702718.23462776420510.0428371531703015.85878787  420623.5613157
1703210.92955251420639.472820996
#Sta/Elev= 30
       0 1182.37    14.9 1175.39    23.4 1170.69    49.1 1154.36    70.5 1139.13
     109 1118.87   113.3  1117.9   121.9 1117.14   198.6 1114.65   207.5 1113.84
   214.1 1114.63   224.6 1115.59   253.9  1115.3     306 1116.88   314.5 1118.13
   330.8 1123.47   346.9 1123.79   350.9 1125.66   358.9 1133.83   362.9 1137.22
   367.9 1140.35   379.1 1146.57   399.1 1158.85   423.1 1170.86   459.3 1188.38
   463.3 1189.78   475.3 1191.64   483.3 1195.85   495.4 1200.75   514.3 1207.21
#Mann= 4 ,-1,0
       0      .1       0   198.6    .045       0   214.1     .06       0
  388.54      .1       0
Bank Sta=198.6,214.1
XS Rating Curve= 0 ,0
Exp/Cntr(USF)=0,0
Exp/Cntr=0.3,0.1

Type RM Length L Ch R = 1 ,8853    ,26.2,26,25.8
BEGIN DESCRIPTION:
Structure 10 XS 3
END DESCRIPTION:
XS GIS Cut Line= 6
1702571.26227623420781.3533548451702745.11608054420722.684423977
1702796.78779947420736.1406007821702846.30653011420760.899966102
1702889.90454296420779.2003665561703100.89739525420983.734253984
#Sta/Elev= 30
       0 1166.32    26.2 1155.22    38.9 1152.48    47.3 1147.11    55.8  1140.2
      60 1137.93    68.4 1135.45    76.9 1131.78    85.3 1130.77      98 1126.88
   108.6 1124.72   114.9 1123.72   144.4 1122.67   211.4 1116.49   289.8 1114.04
   302.9 1111.68   307.2 1110.46   311.6 1110.37   315.9 1111.68   323.9 1114.01
   341.4 1115.38   361.8 1115.16   381.6 1116.53   444.9 1118.56   497.6 1121.89
   542.9 1123.27   565.6 1124.82   582.5 1127.35   599.5 1132.84   633.4 1149.56
#Mann= 5 ,-1,0
       0      .1       0   302.9    .045       0   315.9      .1       0
  339.53     .06       0  479.53      .1       0
Bank Sta=302.9,315.9
XS Rating Curve= 0 ,0
Exp/Cntr(USF)=0,0
Exp/Cntr=0.3,0.1

Type RM Length L Ch R = 1 ,8827    ,37.4,37.1,36.3
BEGIN DESCRIPTION:
Structure 10 XS 2
END DESCRIPTION:
XS GIS Cut Line= 6
1702575.56825281420801.2684965161702740.81010396420743.676059792
1702789.25234046420756.5939895251702837.15632988420785.659331422
1702881.83083688420802.883237732 1703082.5969948420997.190430789
#Sta/Elev= 30
       0 1169.12    34.5 1156.37    48.1 1149.19    75.1 1133.47    89.5 1131.35
   102.2 1126.86   107.8 1125.56   123.5 1123.37   144.6 1122.59   178.4 1119.81
   215.7 1115.59   284.3 1113.21   292.9 1111.47   297.2 1110.32   301.5 1110.14
  306.471111.491   314.3  1113.5   327.2 1114.49   354.5 1114.34   417.7 1116.91
   463.7 1120.63   490.2 1121.79   512.9 1122.02   532.7 1123.38   546.8 1125.75
   555.7 1128.26   569.4 1134.33   583.6 1138.59   597.7 1145.98   608.4 1150.57
#Mann= 5 ,-1,0
       0      .1       0   292.9    .045       0  306.47      .1       0
  339.04     .06       0  479.04      .1       0
Bank Sta=292.9,306.47
XS Rating Curve= 0 ,0
Exp/Cntr(USF)=0,0
Exp/Cntr=0.3,0.1

Type RM Length L Ch R = 1 ,8789    ,37.6,37,35.3
BEGIN DESCRIPTION:
Structure 9 XS 4 AND Structure 10 XS 1
END DESCRIPTION:
XS GIS Cut Line= 4
1702603.02763473420800.1621480361702725.62835673420795.377729617
1702902.65183825 420843.221913811703056.94933227420994.529146323
#Sta/Elev= 30
       0 1159.85    17.1  1151.2    37.1 1142.83    41.1 1140.51    45.1 1137.36
    49.1 1135.33    65.1 1133.74    81.1    1128    97.2 1123.27   104.7 1122.18
   125.3  1120.8   133.6 1119.35     146  1116.2   166.7 1114.05     233 1112.28
  239.051110.679   241.3 1109.82   249.5  1110.7   278.6 1113.85   295.2 1113.72
   330.8 1115.23   358.5  1118.5   369.7 1118.45   414.6 1120.26   467.9  1123.3
   477.7 1125.28   483.4  1127.1   490.8 1130.08   498.6  1134.4   522.2 1142.74
#Mann= 5 ,-1,0
       0      .1       0  239.05    .045       0   249.5      .1       0
  292.69     .06       0  426.07      .1       0
Bank Sta=239.05,249.5
XS Rating Curve= 0 ,0
Exp/Cntr(USF)=0,0
Exp/Cntr=0.3,0.1

Type RM Length L Ch R = 1 ,8753    ,37.4,37.1,37.5
BEGIN DESCRIPTION:
Structure 9 XS 3
END DESCRIPTION:
XS GIS Cut Line= 4
 1702595.2529548420810.329037177 1702693.9315847420858.173221371
1702893.08300141   420865.3498491703044.39023392421004.696035464
#Sta/Elev= 30
       0 1163.52    17.3 1157.29      41 1149.78    54.3 1143.36    58.7 1142.19
    68.2  1140.9    83.1 1132.45    98.8 1126.12   115.9 1116.91   123.9 1114.41
   131.9 1113.25   156.6 1112.29   243.9 1112.08   247.9 1111.74   253.1 1110.34
   255.9 1109.28   259.9 1108.98   263.1 1110.45     268 1112.18   287.9  1113.5
     304 1113.78   319.6 1116.21   401.1 1120.34   432.7 1120.58   463.4 1123.46
   470.8 1124.94     479 1127.68   487.1 1131.36     503 1139.78   514.6 1144.59
#Mann= 5 ,-1,0
       0      .1       0   253.1    .045       0   263.1      .1       0
  308.95     .06       0  438.95      .1       0
Bank Sta=253.1,263.1
XS Rating Curve= 0 ,0
Exp/Cntr(USF)=0,0
Exp/Cntr=0.3,0.1

Type RM Length L Ch R = 1 ,8715    ,209.7,215.7,218.8
BEGIN DESCRIPTION:
Structure 9 XS 2
END DESCRIPTION:
XS GIS Cut Line= 4
1702585.08606566 420843.221913811702690.34327089420896.448568726
1702885.90637378420901.8310394481703027.64476945421035.196702888
#Sta/Elev= 30
       0 1170.05    11.8 1165.11    30.3 1158.93    34.8 1156.76    43.7 1150.07
    53.8 1148.88    57.2 1147.81    75.1 1136.07    98.5 1124.21   115.5 1113.38
   119.7 1111.94   131.7 1110.52   143.7 1111.13   163.7 1110.86   231.8  1111.9
   259.8 1110.75   267.7 1108.66   271.8 1108.81  279.151110.683   295.8 1113.22
   311.8 1113.42   316.6 1114.73   327.6 1116.27   381.7 1118.45   416.8 1118.58
   450.1 1122.31   455.7 1124.15   469.9 1131.26   492.5 1144.39   508.2 1152.48
#Mann= 5 ,-1,0
       0      .1       0  217.95     .06       0   259.8    .045       0
  279.15     .06       0  423.59      .1       0
Bank Sta=259.8,279.15
XS Rating Curve= 0 ,0
Exp/Cntr(USF)=0,0
Exp/Cntr=0.3,0.1

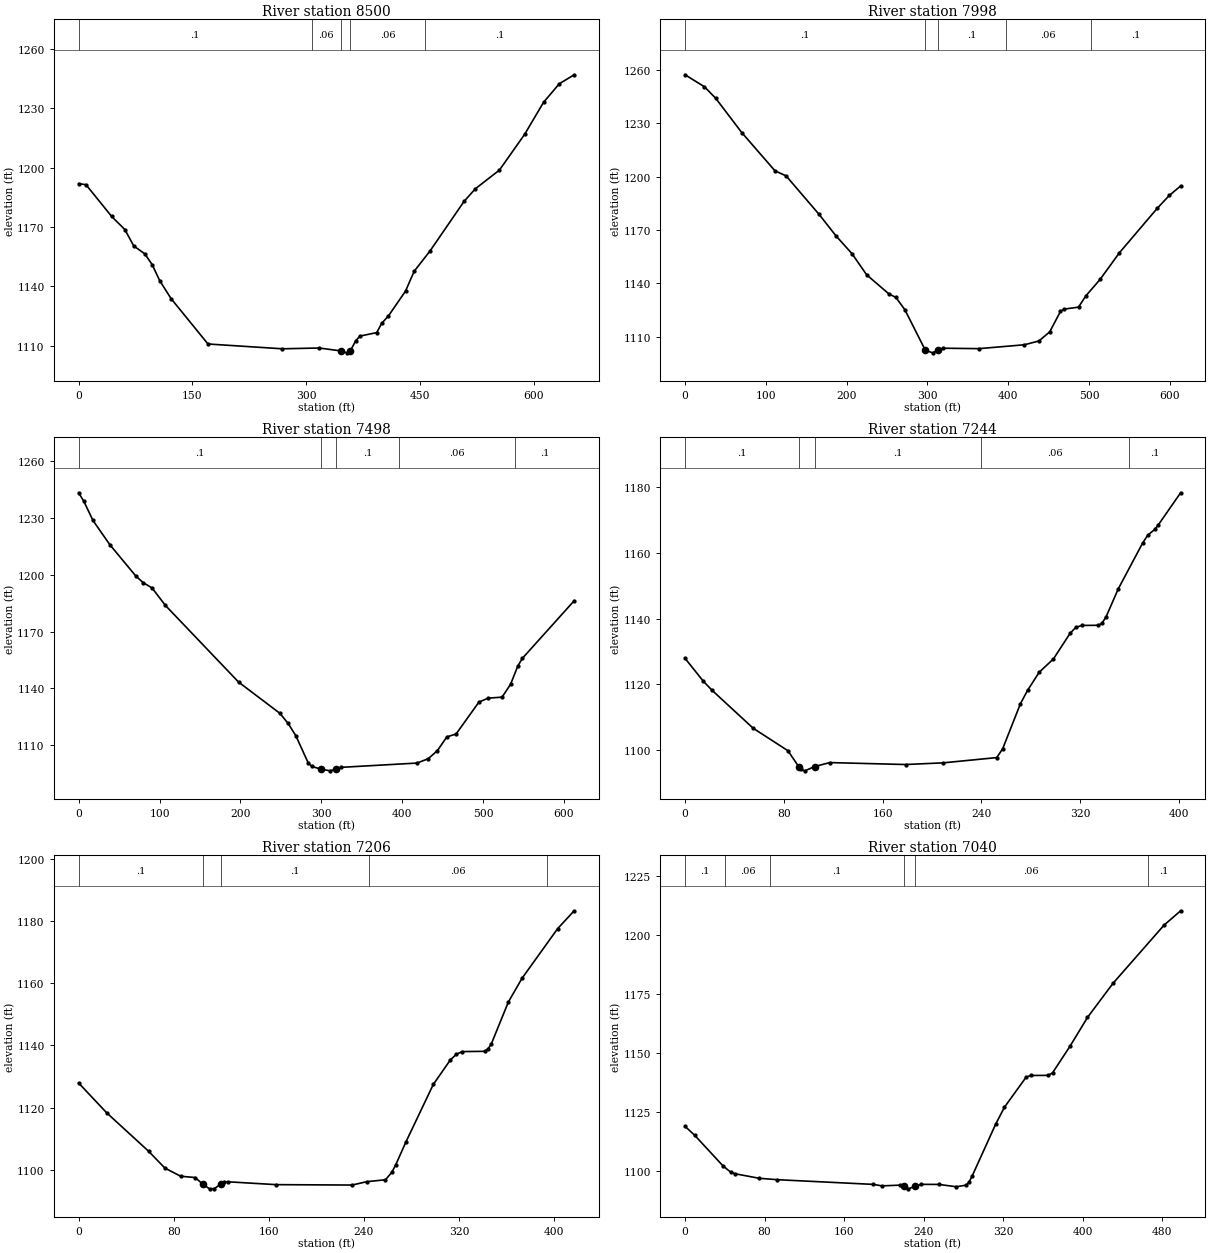
Type RM Length L Ch R = 1 ,8500    ,501.4,502.1,499.3
BEGIN DESCRIPTION:
Structure 9 XS 1
END DESCRIPTION:
XS GIS Cut Line= 6
1702532.14335984420887.6814884991702622.54869084420949.672834337
1702702.32149717 421015.62972343 1702764.6691415421072.220489502
 1702843.3740366421133.9470720891703048.37329851 421287.69774884
#Sta/Elev= 30
       0 1191.86     9.7 1191.34    43.6 1175.27      61 1168.65    72.7 1160.38
    87.3 1156.39      97 1150.93     107  1142.8     122 1133.73   170.6 1110.83
   268.8  1108.4   317.1 1108.81   345.6 1107.35   354.1 1106.36  358.391107.393
   365.5 1112.47   371.2 1114.84   393.2 1116.59   399.7 1121.27   408.3 1124.84
   431.2 1137.59   442.6 1147.61   463.3 1157.75   508.3 1182.86   523.3 1189.29
     555 1198.71   588.3  1216.8   613.3 1233.01     634 1242.35   653.6 1246.88
#Mann= 5 ,-1,0
       0      .1       0  307.33     .06       0   345.6    .045       0
  358.39     .06       0  457.35      .1       0
Bank Sta=345.6,358.39
XS Rating Curve= 0 ,0
Exp/Cntr(USF)=0,0
Exp/Cntr=0.3,0.1

Type RM Length L Ch R = 1 ,7998    ,496.6,500,501.1
XS GIS Cut Line= 6
1702247.27024193421304.0654982631702329.14967135421350.987648502
1702560.61705618 421474.797768341702626.75143833421510.171385258
 1702705.3464255421548.7507044231702790.19730568421588.886122838
#Sta/Elev= 30
       0 1257.24      24 1250.48    37.9 1244.02    70.1 1224.78   111.3 1203.24
     125 1200.43   165.8  1178.8   186.4 1166.89   206.6 1156.68   224.7 1144.82
     252 1134.17     261 1132.08   272.1 1125.12   297.3 1102.44   306.4 1100.97
   312.4 1102.32   319.4 1103.57   363.7 1103.33   419.9  1105.5   437.8 1107.63
   451.2 1112.71   464.6 1124.26     469 1125.53   486.9 1126.66   495.8 1132.89
   513.6 1142.24   537.6 1157.26   584.4 1182.22   599.4 1189.48   613.3 1194.75
#Mann= 5 ,-1,0
       0      .1       0   297.3    .045       0   312.4      .1       0
  396.87     .06       0  501.87      .1       0
Bank Sta=297.3,312.4
XS Rating Curve= 0 ,0
Exp/Cntr(USF)=0,0
Exp/Cntr=0.3,0.1

Type RM Length L Ch R = 1 ,7498    ,259.2,253.3,252.7
BEGIN DESCRIPTION:
Structure 8 XS 4
END DESCRIPTION:
XS GIS Cut Line= 6
 1701957.1120296421583.8903979211702022.85336792 421650.72687842
  1702084.211841421713.1079872551702136.80523975421766.577368513
1702320.88065901421953.7200388461702386.62199734422020.556519344
#Sta/Elev= 30
       0 1243.39     6.5 1238.84    17.7 1228.77    38.5 1215.98    70.5 1199.48
    79.5 1195.96    90.7  1193.1   107.2 1183.87   197.7 1143.32   248.7 1126.82
     259 1121.43   268.5 1114.94   283.8 1100.56   288.3  1098.7   299.6 1097.31
   310.9  1096.4     318 1097.34   323.7 1098.23   418.4 1100.51   432.1 1102.82
   443.5 1107.11   455.1 1114.34   466.5 1115.86   494.8 1132.75   506.2 1134.83
   523.4 1135.36   533.9 1142.17   542.8 1151.75   548.5 1155.89   612.5 1186.31
#Mann= 5 ,-1,0
       0      .1       0   299.6    .045       0     318      .1       0
  396.25     .06       0  538.75      .1       0
Bank Sta=299.6,318
XS Rating Curve= 0 ,0
Exp/Cntr(USF)=0,0
Exp/Cntr=0.3,0.1

Type RM Length L Ch R = 1 ,7244    ,37.3,38.3,36.4
BEGIN DESCRIPTION:
Structure 8 XS 3
END DESCRIPTION:
XS GIS Cut Line= 4
 1701910.8551099421908.6223655891701952.05426852421963.111575366
1702012.52400132421974.4081188561702233.13885065422132.559727718
#Sta/Elev= 30
       0 1127.93    14.9 1120.92      22 1118.17    55.1  1106.7    83.3 1099.85
   91.931095.059    93.6 1094.25    96.9 1093.74     105 1095.05   117.2 1096.25
   178.5 1095.66     209 1096.17   252.4 1097.77   257.2 1100.47   271.5  1114.1
   277.3 1118.19   286.8 1123.73   298.3 1127.77   311.7  1135.5   316.3 1137.34
   321.3 1137.95   334.6 1137.99   337.5 1138.56     341 1140.62   350.8 1149.08
   370.5 1162.98   374.7  1165.4   380.5 1167.19   383.3 1168.57   401.3 1178.28
#Mann= 5 ,-1,0
       0      .1       0   91.93    .045       0     105      .1       0
  239.83     .06       0  359.83      .1       0
Bank Sta=91.93,105
XS Rating Curve= 0 ,0
Exp/Cntr(USF)=0,0
Exp/Cntr=0.3,0.1

Type RM Length L Ch R = 1 ,7206    ,164.3,166.3,167.4
BEGIN DESCRIPTION:
Structure 8 XS 2
END DESCRIPTION:
XS GIS Cut Line= 4
1701876.30097688421935.2024679191701930.79018665421994.343195603
1701993.91792969422004.3107339771702217.19078926422160.468835164
#Sta/Elev= 30
       0 1127.91    23.6 1118.32    58.8 1105.96    72.5 1100.54    85.8  1097.9
      98 1097.48   104.5 1095.32   110.1 1093.84   114.2  1093.9  119.42 1095.37
   122.3 1096.07   125.5 1096.11   166.2 1095.19     230 1095.06   242.4 1096.15
   258.1 1096.76   263.4 1099.16   266.7 1101.56   275.3 1108.95   298.3 1127.45
   312.7 1135.37   317.8 1137.19   322.7 1138.03   341.4 1138.12   344.3 1138.89
   347.1 1140.49   361.5 1154.04     373 1161.67   402.9 1177.62   416.8 1183.37
#Mann= 5 ,-1,0
       0      .1       0   104.5    .045       0  119.42      .1       0
  244.33     .06       0  394.33      .1       0
Bank Sta=104.5,119.42
XS Rating Curve= 0 ,0
Exp/Cntr(USF)=0,0
Exp/Cntr=0.3,0.1

Type RM Length L Ch R = 1 ,7040    ,83.2,79.9,76.9
BEGIN DESCRIPTION:
Structure 7 XS 4 AND Structure 8 XS 1
END DESCRIPTION:
XS GIS Cut Line= 3
1701784.59962384422022.9168056081701796.56066989422097.341092131
1702181.30765111422273.434270066
#Sta/Elev= 30
       0    1119     9.7  1115.2    38.1 1102.26    46.2 1099.48    50.3 1098.91
    74.6 1096.99    92.7  1096.4   189.1 1094.41   198.1 1093.78   215.7 1094.08
   220.1 1093.53   224.5 1092.52  231.081093.556   237.7 1094.42   255.2 1094.39
   272.8 1093.41   282.7 1094.08   285.7 1095.42   288.7 1097.89   312.4 1119.91
   321.2 1127.08     343 1139.83   347.6 1140.57   365.2 1140.62   369.6 1141.67
   387.2 1152.96   404.8 1165.19   430.5 1179.65   481.8  1204.3   498.5 1210.39
#Mann= 6 ,-1,0
       0      .1       0      40     .06       0   85.38      .1       0
   220.1    .045       0  231.08     .06       0  465.38      .1       0
Bank Sta=220.1,231.08
XS Rating Curve= 0 ,0
Exp/Cntr(USF)=0,0
Exp/Cntr=0.3,0.1

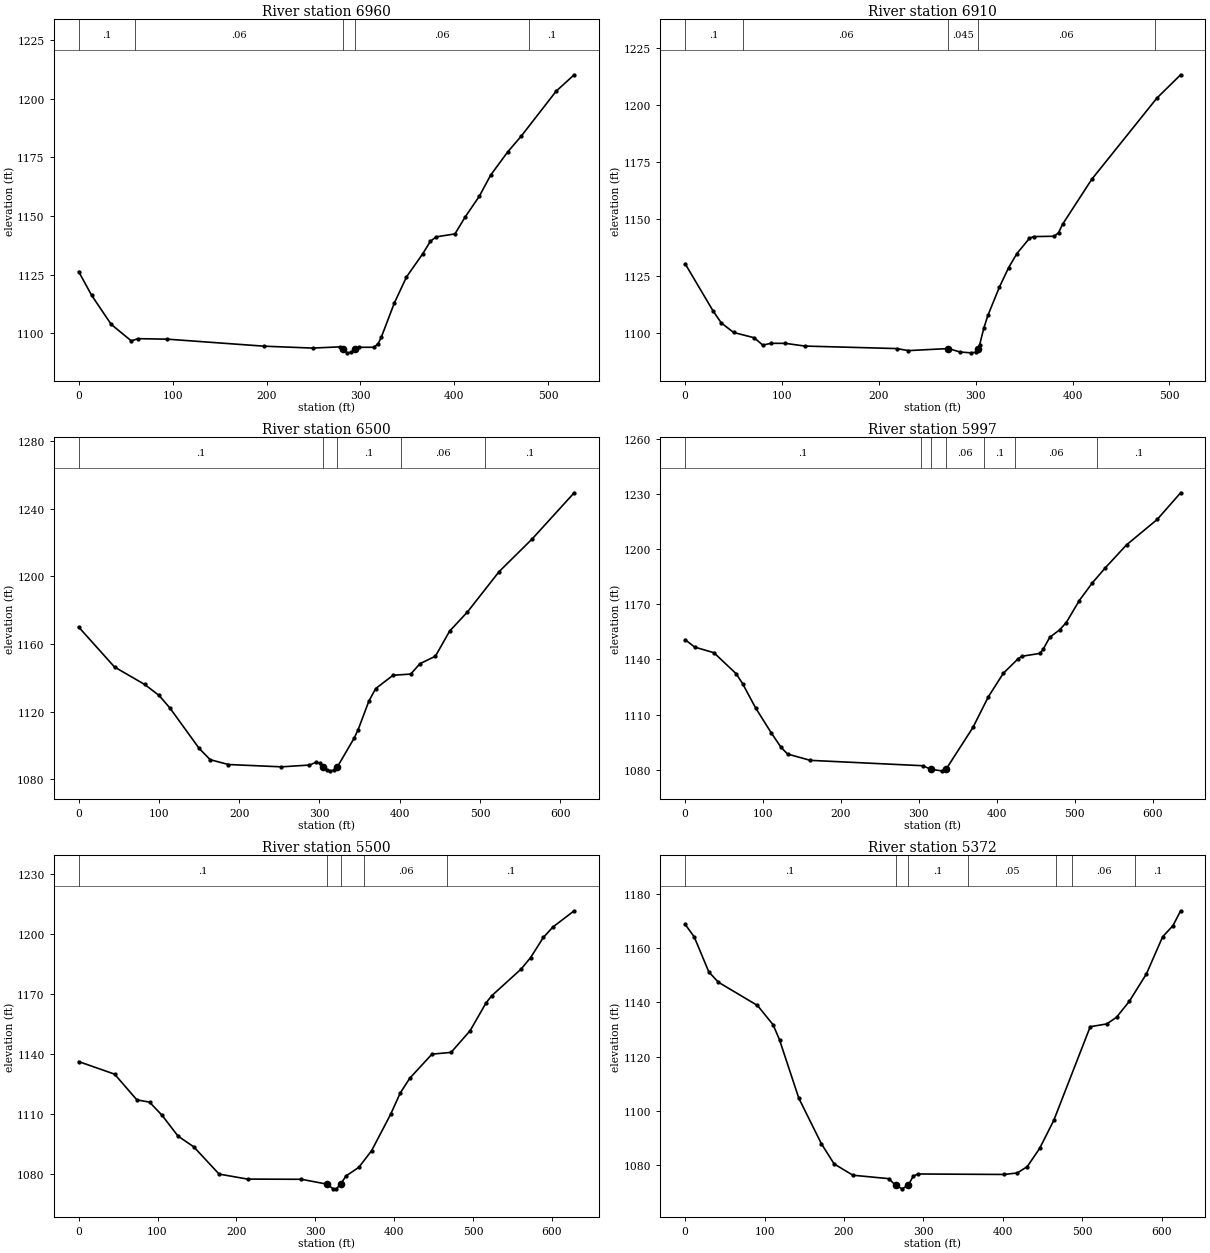
Type RM Length L Ch R = 1 ,6960    ,52.1,49.9,49.1
BEGIN DESCRIPTION:
Structure 7 XS 3
END DESCRIPTION:
XS GIS Cut Line= 6
1701655.74736727422213.8390044141701757.04816138422175.497847161
1701865.38057866422229.6373113311701907.46574069422240.712353968
 1701942.9933857422236.5254644161702145.97050821422317.444916018
#Sta/Elev= 30
       0 1126.37    13.7 1116.32    34.6 1103.86      56 1096.81    63.3 1097.74
    94.5 1097.53   197.7 1094.53   249.1 1093.73   277.9 1094.25   281.51093.167
     286  1091.7     290  1091.9     294 1093.18     298 1094.06   314.5 1094.08
   318.8  1095.6   322.2 1098.37     336 1112.88     349 1124.04   366.2 1133.88
   374.5 1139.29   380.7 1141.16   400.6 1142.41   411.2 1149.46   426.5 1158.45
   438.6 1167.48   456.6 1177.29   471.1 1184.07   508.3 1203.26   527.5 1210.26
#Mann= 5 ,-1,0
       0      .1       0      60     .06       0   281.5    .045       0
     294     .06       0     479      .1       0
Bank Sta=281.5,294
XS Rating Curve= 0 ,0
Exp/Cntr(USF)=0,0
Exp/Cntr=0.3,0.1

Type RM Length L Ch R = 1 ,6910    ,401.7,409.9,413.9
BEGIN DESCRIPTION:
Structure 7 XS 2
END DESCRIPTION:
XS GIS Cut Line= 6
 1701656.5977597  422243.12479411701739.44014942422212.905334781
1701859.58594551 422279.596513941701901.67110753422290.671556577
1701937.19875255422286.4846670251702129.54383413422361.423595603
#Sta/Elev= 30
       0 1130.39      29 1109.59    37.4  1104.4    50.1 1100.24    71.4 1097.91
    80.2 1094.68    88.5 1095.48   103.5 1095.47   123.6 1094.28   218.5 1093.18
   230.6 1092.29   271.8 1093.19   283.9 1091.67   295.1 1091.31     300 1091.56
  302.031093.174   304.1 1094.82   308.3 1101.99   312.6 1107.71   324.4 1120.03
     334 1128.65   342.6 1134.84   355.5 1141.49   359.8 1142.25   381.3 1142.41
   385.6 1144.03   389.9 1147.78   419.9  1167.4   487.1 1202.96   511.6 1213.17
#Mann= 5 ,-1,0
       0      .1       0      60     .06       0   271.8    .045       0
  302.03     .06       0  485.16      .1       0
Bank Sta=271.8,302.03
XS Rating Curve= 0 ,0
Exp/Cntr(USF)=0,0
Exp/Cntr=0.3,0.1

Type RM Length L Ch R = 1 ,6500    ,498,502.9,502.7
BEGIN DESCRIPTION:
Structure 7 XS 1
END DESCRIPTION:
XS GIS Cut Line= 6
1701549.55805467422526.6398247631701710.33726068 422617.32665126
1701779.51822467422649.4991590831701940.45819151422718.577761084
1702019.54530367422756.0681716651702102.50609575422799.965065509
#Sta/Elev= 30
       0 1170.09    44.7 1146.42    82.2 1136.11   100.2 1129.61   113.8  1122.1
   150.2 1098.23   163.9 1091.57   186.6 1088.71   252.7 1087.34   287.6  1088.4
   296.2  1090.1   300.6  1089.5   304.9  1087.2   309.3 1085.37   313.6 1084.97
   317.9 1085.23   322.3 1087.28   343.2 1104.24   348.3 1109.38   361.5 1126.09
     370 1133.62   391.8 1141.55   413.8 1142.23   425.2 1148.37   444.5 1152.79
   462.2 1167.65   484.4 1178.97   523.8 1202.82     565 1222.17   617.4 1249.52
#Mann= 5 ,-1,0
       0      .1       0   304.9    .045       0   322.3      .1       0
  401.08     .06       0  506.06      .1       0
Bank Sta=304.9,322.3
XS Rating Curve= 0 ,0
Exp/Cntr(USF)=0,0
Exp/Cntr=0.3,0.1

Type RM Length L Ch R = 1 ,5997    ,502.6,497.1,486.3
XS GIS Cut Line= 6
1701427.86702509422990.2153411661701618.50312676423037.174892917
1701684.31795576423076.881178334 1701826.1359136423180.261220917
1701911.28010026423208.6971876771702006.65458143423227.295575678
#Sta/Elev= 30
       0 1150.74    12.5  1146.7      37 1143.66    65.6 1132.21    73.8 1126.86
    90.4 1113.71   110.8 1099.95   123.2 1092.18   131.6 1088.56   160.7 1085.14
     305 1082.22   315.6 1080.25   329.2 1079.44  335.021080.375   369.4 1103.01
   389.3 1119.77   408.4 1132.46   427.5 1140.41   432.3 1141.73   455.3 1143.29
   459.5  1145.5     468 1152.02   480.6 1156.07   489.1 1159.99   505.9 1172.02
   522.8  1181.7   539.4 1189.85   566.6 1202.32   605.9 1216.11     636 1230.62
#Mann= 7 ,-1,0
       0      .1       0  303.33     .06       0   315.6    .045       0
  335.02     .06       0  383.64      .1       0  423.64     .06       0
  529.01      .1       0
Bank Sta=315.6,335.02
XS Rating Curve= 0 ,0
Exp/Cntr(USF)=0,0
Exp/Cntr=0.3,0.1

Type RM Length L Ch R = 1 ,5500    ,121.8,128.3,137.2
BEGIN DESCRIPTION:
Structure 6 XS 4
END DESCRIPTION:
XS GIS Cut Line= 6
1701446.69605568423567.4349872621701546.94224626423577.475649595
1701639.71338618423584.0048360081701717.38875575423579.836209178
 1701816.7537145 423564.831646011702070.85130343    423531.68998
#Sta/Elev= 30
       0 1136.16    45.6 1129.86    73.8 1117.03    89.9 1115.88   105.9 1109.25
     126 1098.91     146 1093.54   178.1 1079.93   214.2 1077.43   282.4 1077.33
   314.7 1074.92   322.8 1072.56   326.9 1072.64  332.341074.984     339    1079
   355.2 1083.28   371.4 1091.59   395.6  1109.8   407.7 1120.39   419.8 1127.81
     448 1139.87   472.2 1140.73   496.4  1151.6   516.6  1165.5     524 1169.13
     561 1182.37   573.1 1188.13   589.2 1198.16   601.3 1203.37   628.3  1211.5
#Mann= 5 ,-1,0
       0      .1       0   314.7    .045       0  332.34      .1       0
  361.54     .06       0  467.03      .1       0
Bank Sta=314.7,332.34
XS Rating Curve= 0 ,0
Exp/Cntr(USF)=0,0
Exp/Cntr=0.3,0.1

Type RM Length L Ch R = 1 ,5372    ,37.3,38.3,38.6
BEGIN DESCRIPTION:
Structure 6 XS 3
END DESCRIPTION:
XS GIS Cut Line= 6
1701478.53380725423698.1701107381701710.97297371423664.443643447
1701721.91128743423682.6741663071701750.16859786423710.019950597
1701839.49815988423757.4193100331702057.35290805423693.612480023
#Sta/Elev= 30
       0 1168.84    11.4 1164.25    29.9 1151.25      42 1147.46    91.1  1138.9
   110.7 1131.81   118.8 1126.25   143.1 1104.71   171.4 1087.98   187.5 1080.49
   211.1 1076.31   256.2 1075.05   264.8 1072.63   273.2 1071.29  280.91 1072.68
     287 1075.93     293 1076.77   401.4 1076.59   418.1 1077.15   430.6  1079.5
   446.1 1086.17   463.9  1096.5   509.8 1131.06   530.6  1132.1   542.9 1134.55
     559 1140.43   580.6 1150.58   600.9 1164.21     614 1168.36   623.6 1173.82
#Mann= 7 ,-1,0
       0      .1       0   264.8    .045       0  280.91      .1       0
  355.46     .05       0  466.58      .1       0  486.58     .06       0
  566.58      .1       0
Bank Sta=264.8,280.91
XS Rating Curve= 0 ,0
Exp/Cntr(USF)=0,0
Exp/Cntr=0.3,0.1