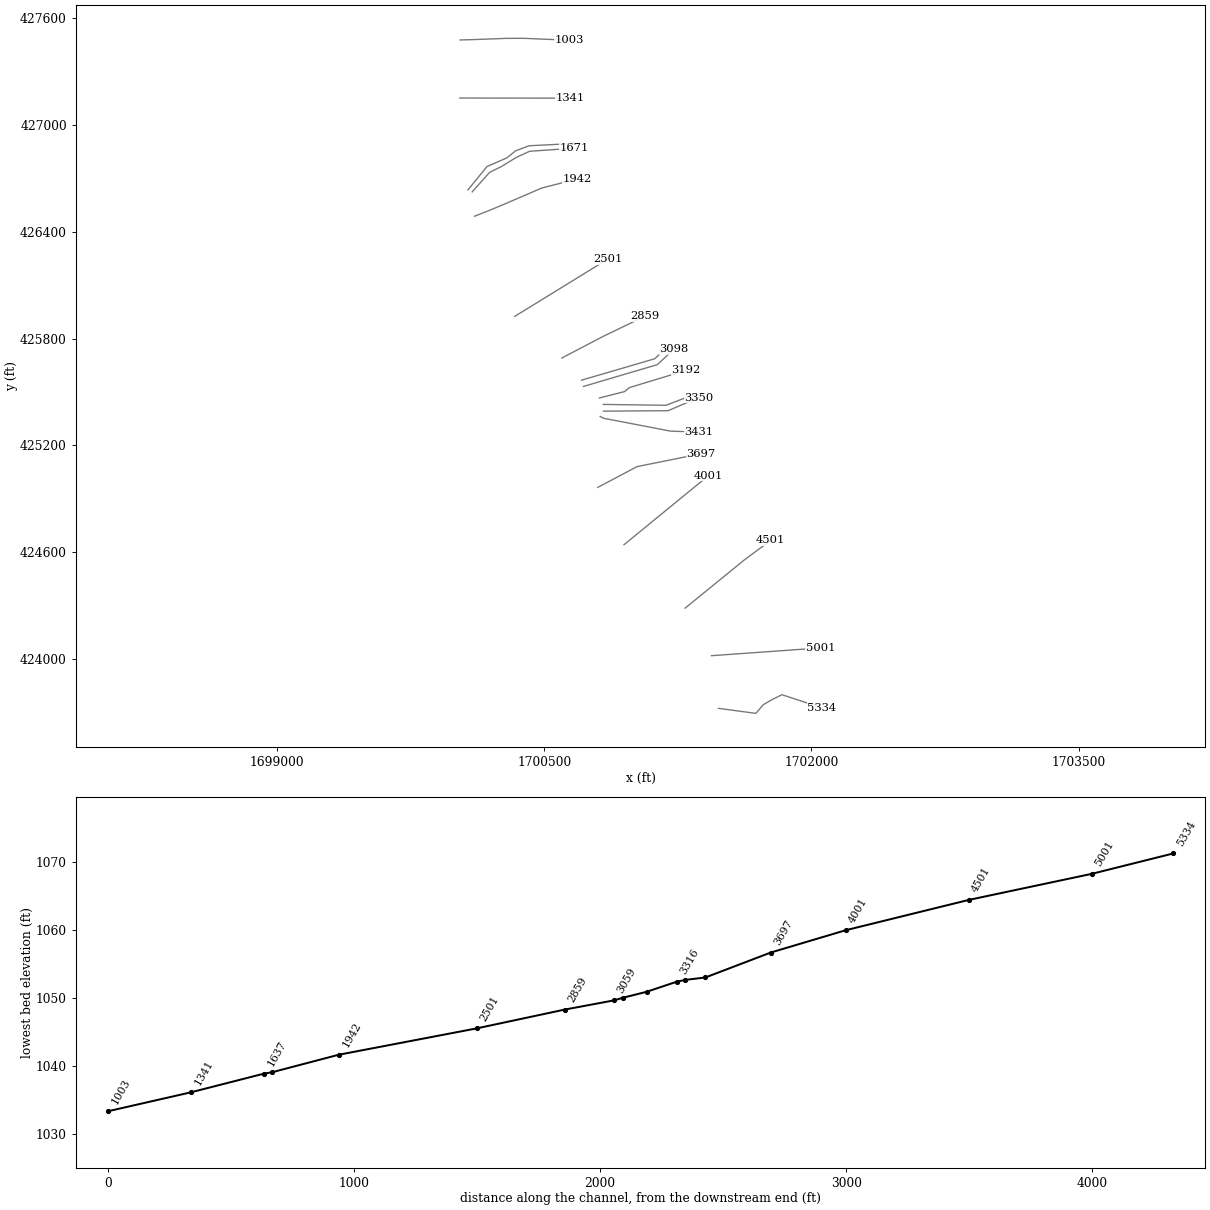
HEC-RAS study RUSHRN2.prj: RUSHRN2

--- RUSHRN2.g01 (geometry) --- (continued)

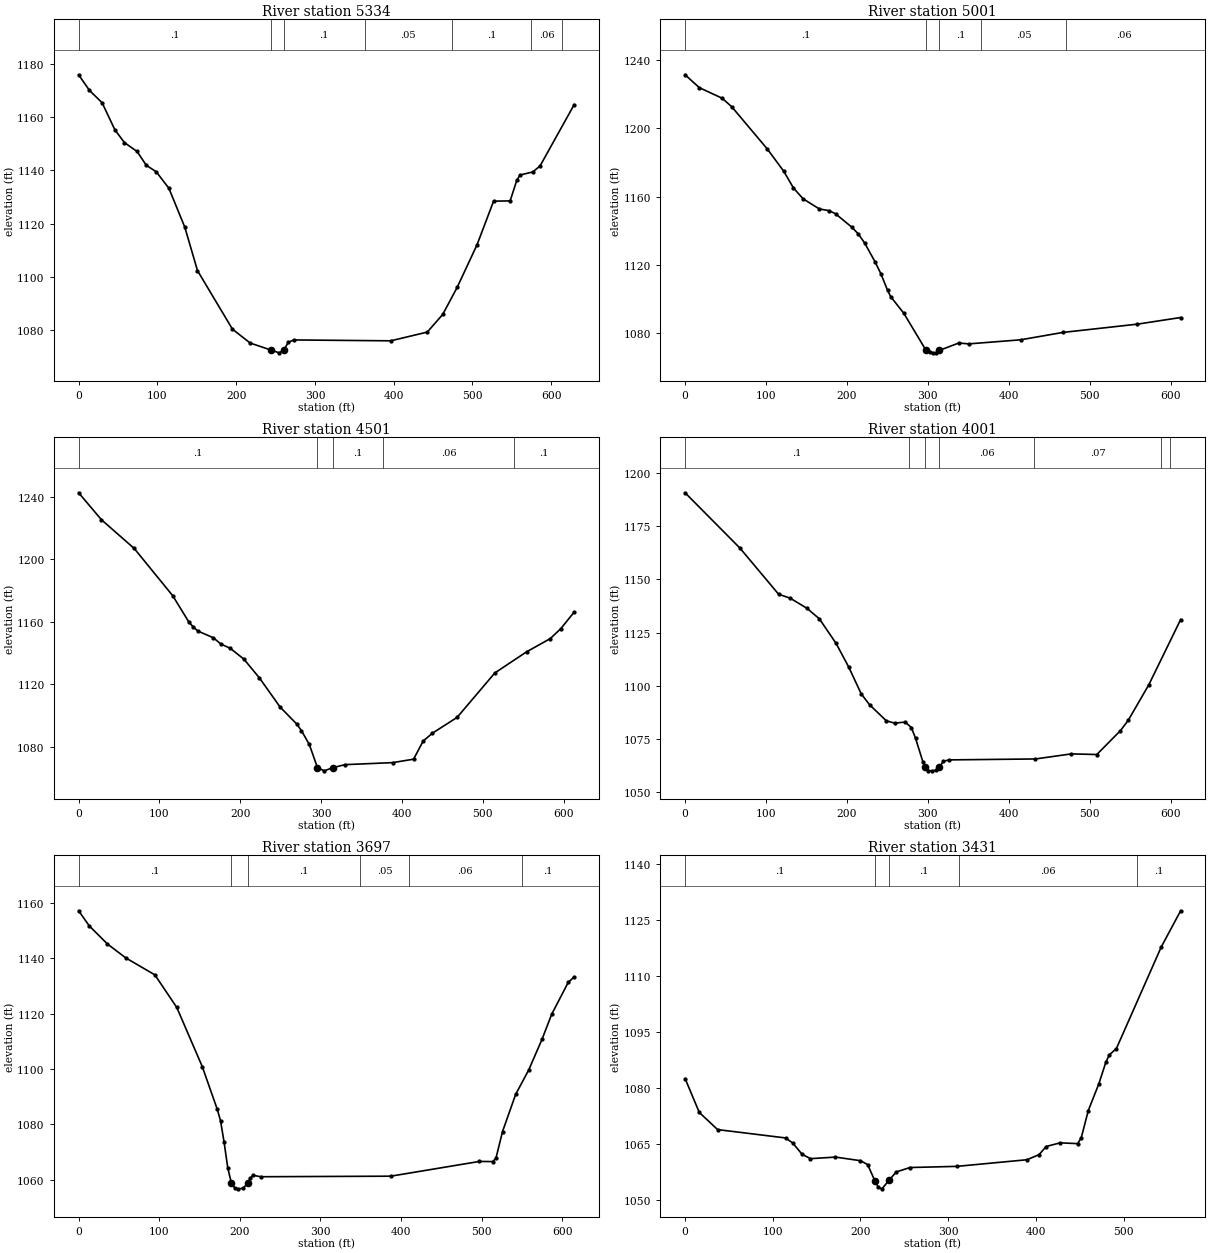
Type RM Length L Ch R = 1 ,5334    ,337.8,332.4,325.2
BEGIN DESCRIPTION:
Structure 6 XS 2
END DESCRIPTION:
XS GIS Cut Line= 6
1701478.53380725423723.6928427421701688.18482014423695.435532309
1701730.11502272423744.6579440311701779.33743444423772.915254464
1701834.02900302423800.2610387541702057.35290805423727.338947314
#Sta/Elev= 30
       0 1176.07    13.7  1170.2    29.8 1165.53      46 1155.34    58.1 1150.53
    74.2 1147.16      86 1141.93    98.5 1139.53   114.6 1133.29   134.8 1118.62
   150.9 1102.26   195.3 1080.19   217.8 1074.97   244.1 1072.34   254.7 1071.28
   260.6 1072.41   266.2 1075.25   273.2 1076.14   396.3 1075.81   442.6  1079.1
   462.2 1085.74   480.5 1095.92   505.7 1111.94   526.8 1128.45   547.8 1128.53
   556.2 1136.26   560.4  1138.3   576.4 1139.43   585.7 1141.67   629.1 1164.81
#Mann= 7 ,-1,0
       0      .1       0   244.1    .045       0   260.6      .1       0
  362.98     .05       0  474.13      .1       0  574.13     .06       0
  614.13      .1       0
Bank Sta=244.1,260.6
XS Rating Curve= 0 ,0
Exp/Cntr(USF)=0,0
Exp/Cntr=0.3,0.1

Type RM Length L Ch R = 1 ,5001    ,494.1,500,504.8
BEGIN DESCRIPTION:
Structure 6 XS 1
END DESCRIPTION:
XS GIS Cut Line= 6
1701438.54056017424019.1712885051701532.05251226424025.848112419
1701619.33022484424032.0823519231701793.88565001424044.550174758
1701955.97259617424056.1272513421702049.48454826424062.806043759
#Sta/Elev= 30
       0 1231.52    17.6 1223.95    45.7 1217.78    57.7 1212.73   101.8 1187.84
   121.9 1174.89   133.9 1165.08   145.9 1158.68     166 1152.73     178 1151.74
     186  1149.9   206.1 1142.03   214.1 1138.06   222.1 1132.64   234.8 1121.68
   242.2 1114.51   250.2    1105   254.2 1101.21   270.3 1091.53  297.651069.836
   302.3 1068.47   306.4 1068.27   310.4 1068.42   314.4 1069.74   338.4 1074.05
   350.5 1073.53   414.6 1075.91   466.9 1080.25     559 1085.11   612.5 1089.01
#Mann= 5 ,-1,0
       0      .1       0  297.65    .045       0   314.4      .1       0
  366.25     .05       0  471.25     .06       0
Bank Sta=297.65,314.4
XS Rating Curve= 0 ,0
Exp/Cntr(USF)=0,0
Exp/Cntr=0.3,0.1

Type RM Length L Ch R = 1 ,4501    ,499.5,500,499.8
XS GIS Cut Line= 6
1701290.73475343424286.2540876721701363.44326942424345.436384007
1701489.47156067424448.018527925 1701625.1934021424558.492716417
1701695.58040042424610.6267985111701771.63536642424666.267435253
#Sta/Elev= 30
       0 1242.48    28.2 1225.23    68.8 1206.81   116.3 1176.65   136.2 1159.88
   141.9  1156.5   147.6 1153.93   166.8 1149.62     176  1145.6   187.4 1142.95
   204.5 1135.94   223.6 1123.98   249.3 1105.26   269.9 1094.37   275.6 1090.22
   285.4 1081.32   295.5 1066.46     304 1064.43   314.1 1066.41   329.6  1068.4
   388.6 1069.69   414.4  1071.9   426.2 1083.45   437.7 1088.53   468.3 1098.68
   514.9  1127.1   554.2 1140.63   583.6 1149.12   596.6 1155.52   613.1 1166.07
#Mann= 5 ,-1,0
       0      .1       0   295.5    .045       0   314.1      .1       0
  376.25     .06       0  538.84      .1       0
Bank Sta=295.5,314.1
XS Rating Curve= 0 ,0
Exp/Cntr(USF)=0,0
Exp/Cntr=0.3,0.1

Type RM Length L Ch R = 1 ,4001    ,306.7,304.3,302.6
XS GIS Cut Line= 6
1700947.64521651424642.3140710891701087.92511967 424757.08811976
 1701145.9719196424804.5811350051701223.36809026424867.904499173
1701349.13621143424970.8052120061701421.69479334425030.171563089
#Sta/Elev= 30
       0 1190.79    67.8 1164.76   115.6 1143.05   129.8 1141.22   150.5 1136.48
     166 1131.48   186.7 1119.88   202.2 1108.83   217.7  1096.2     228 1091.06
   248.7 1083.52     259 1082.41     272 1082.92   279.7 1080.32   284.9 1075.22
   294.1 1063.99  296.891061.775   300.4 1060.12   305.5 1059.97   310.7 1060.25
  314.32 1061.82   319.3 1064.44     326 1065.12   433.1 1065.56   477.3 1067.94
   508.9 1067.65   538.1 1078.89   547.7 1083.72   573.3 1100.56   612.5 1131.14
#Mann= 7 ,-1,0
       0      .1       0  276.25     .06       0  296.89    .045       0
  314.32     .06       0  431.25     .07       0  588.75     .06       0
  598.75      .1       0
Bank Sta=296.89,314.32
XS Rating Curve= 0 ,0
Exp/Cntr(USF)=0,0
Exp/Cntr=0.3,0.1

Type RM Length L Ch R = 1 ,3697    ,273.7,265.5,259.9
XS GIS Cut Line= 3
1700800.48498972424964.1966308371701021.07431632 425080.87197714
1701379.30409052425152.882542437
#Sta/Elev= 30
       0 1157.11    13.2 1151.65    35.8  1145.1    58.4 1140.11    94.6 1133.97
   121.8 1122.19   153.4 1100.84   171.8 1085.61   176.1 1081.27   180.4 1073.71
   185.1 1064.22   189.6 1058.72   194.2 1056.84   198.3 1056.69   204.2 1056.89
   209.6 1058.76   213.1 1060.63   216.8 1061.57   225.8 1061.06   387.3 1061.26
   497.4 1066.59   513.8 1066.53   517.8  1067.7     526 1077.38   542.3 1090.81
   558.6 1099.69     575  1110.7   587.2 1119.87   607.6 1131.28   614.9 1133.21
#Mann= 6 ,-1,0
       0      .1       0   189.6    .045       0   209.6      .1       0
  349.55     .05       0  409.55     .06       0  549.55      .1       0
Bank Sta=189.6,209.6
XS Rating Curve= 0 ,0
Exp/Cntr(USF)=0,0
Exp/Cntr=0.3,0.1

Type RM Length L Ch R = 1 ,3431    ,79.7,81.8,82.7
BEGIN DESCRIPTION:
Structure 5 XS 4
END DESCRIPTION:
XS GIS Cut Line= 4
1700813.76931268 425362.452645161700833.56739068425352.192653353
1701209.82085019425279.8913233831701369.44595131 425275.06751874
#Sta/Elev= 30
       0 1082.51    16.2 1073.44    37.1 1068.86   114.5 1066.63   122.6 1065.31
   133.5 1062.24     143 1061.09   171.5 1061.51     200 1060.55   208.2 1059.49
   216.3 1055.22   220.4 1053.39   224.5 1053.02   232.4 1055.27   240.8 1057.54
   256.5 1058.72     310 1059.03   389.8  1060.8   403.7 1062.17   411.7 1064.34
   427.7 1065.32   447.7 1065.11   451.8 1066.71   459.8 1073.96   471.8 1081.09
   479.8 1086.86   483.8 1088.86   491.8 1090.51     543  1117.7   565.1 1127.37
#Mann= 5 ,-1,0
       0      .1       0   216.3    .045       0   232.4      .1       0
   312.3     .06       0  515.44      .1       0
Bank Sta=216.3,232.4
XS Rating Curve= 0 ,0
Exp/Cntr(USF)=0,0
Exp/Cntr=0.3,0.1

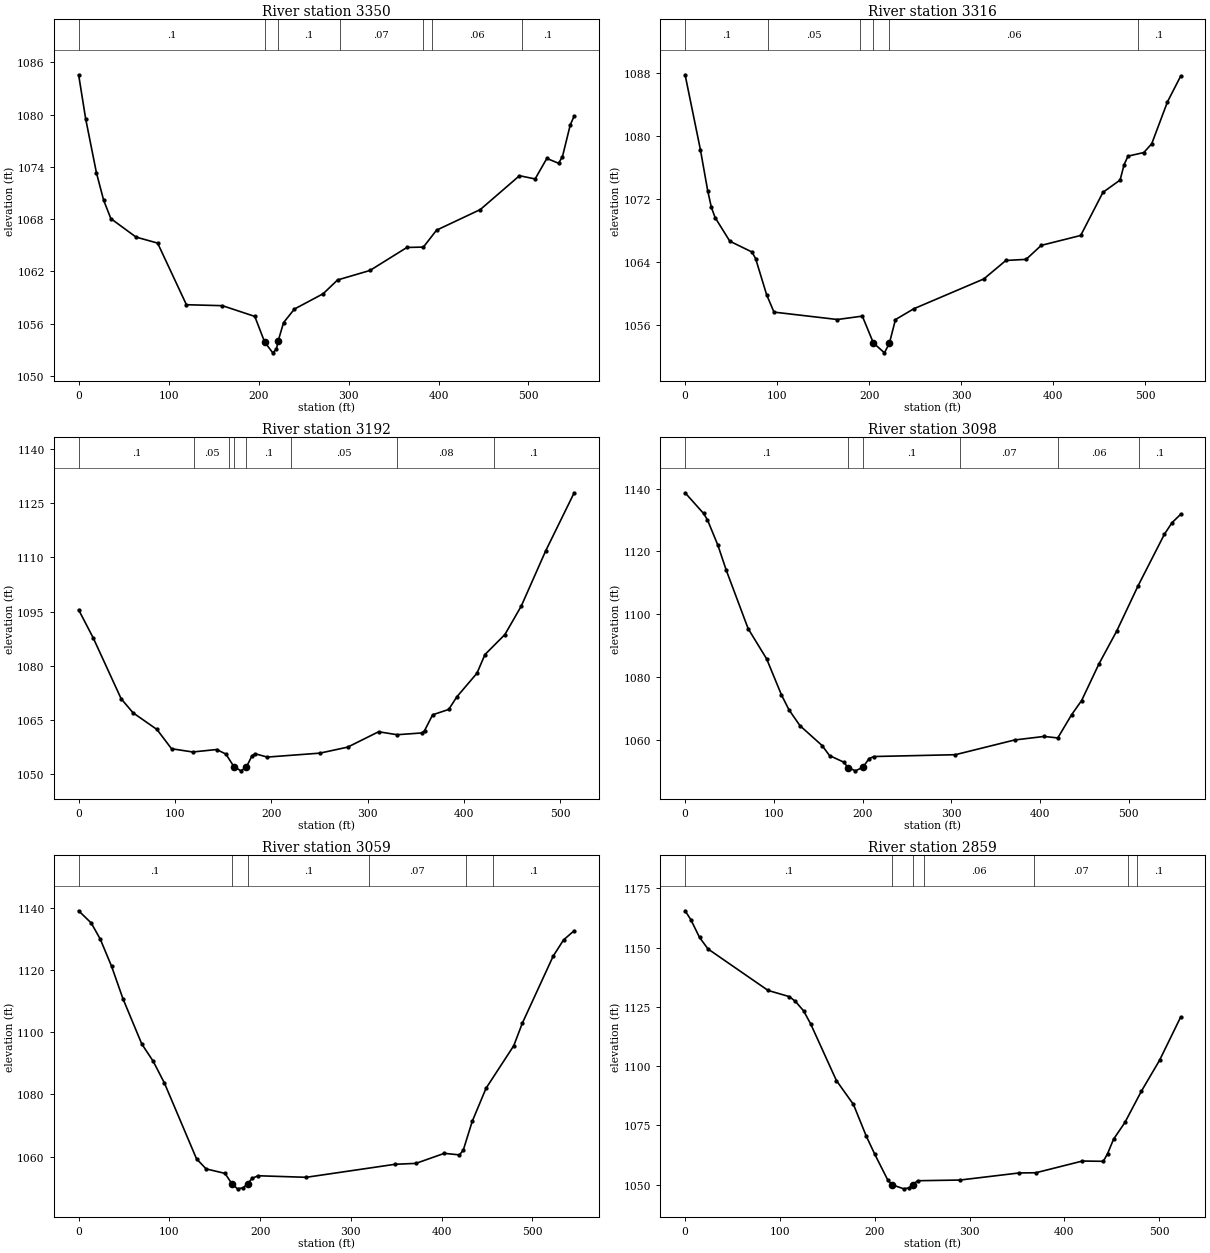
Type RM Length L Ch R = 1 ,3350    ,33.6,33.4,33.2
BEGIN DESCRIPTION:
Structure 5 XS 3
END DESCRIPTION:
XS GIS Cut Line= 3
1700832.33900001425392.2634362431701194.94409969425394.724556829
1701368.04291425425468.558174412
#Sta/Elev= 30
       0 1084.56     7.8 1079.52    19.8 1073.31    27.8 1070.17    35.8 1068.06
    63.8 1065.94    87.8 1065.25   119.8 1058.18   159.8 1058.07   195.8 1056.84
   206.7 1053.91   215.8 1052.66   219.8 1053.08   221.91054.062   227.8 1056.13
   239.8 1057.68   271.8 1059.44   287.8 1061.02   323.8 1062.11   364.9 1064.75
   383.2 1064.79   397.8 1066.73   446.5  1069.1     490 1072.98   507.4 1072.61
   520.4 1074.96   533.5 1074.41   537.8 1075.18   546.5 1078.83   550.8 1079.82
#Mann= 7 ,-1,0
       0      .1       0   206.7    .045       0   221.9      .1       0
     290     .07       0  382.61      .1       0  392.61     .06       0
  492.61      .1       0
Bank Sta=206.7,221.9
XS Rating Curve= 0 ,0
Exp/Cntr(USF)=0,0
Exp/Cntr=0.3,0.1

Type RM Length L Ch R = 1 ,3316    ,114.9,123.9,127.5
BEGIN DESCRIPTION:
Structure 5 XS 2
END DESCRIPTION:
XS GIS Cut Line= 3
1700831.51862648425430.0006185631701183.45887029425425.078377391
1701357.37805837425492.349006744
#Sta/Elev= 30
       0 1087.78    16.6 1078.27    24.6 1073.01    28.6  1070.9    32.6 1069.62
    48.6 1066.61    72.6 1065.24    76.6 1064.41    88.6  1059.8    96.6 1057.59
   165.5 1056.65   192.6 1057.08   204.6 1053.67   216.6 1052.41  221.961053.616
   228.6 1056.64   248.6 1058.02   324.6 1061.81   348.6 1064.16   370.6  1064.3
     387 1066.08   429.9 1067.34   454.1 1072.83   472.7 1074.39   477.1 1076.36
   481.3 1077.43   498.5 1077.89   507.1 1079.01   524.2 1084.34   538.5  1087.6
#Mann= 6 ,-1,0
       0      .1       0      90     .05       0     190     .06       0
   204.6    .045       0  221.96     .06       0  491.97      .1       0
Bank Sta=204.6,221.96
XS Rating Curve= 0 ,0
Exp/Cntr(USF)=0,0
Exp/Cntr=0.3,0.1

Type RM Length L Ch R = 1 ,3192    ,97.8,94.2,90.9
BEGIN DESCRIPTION:
Structure 4 XS 5 AND Structure 5 XS 1
END DESCRIPTION:
XS GIS Cut Line= 4
 1700809.3685412425466.0970538261700951.29316167425502.193489089
1700977.54511459425524.3435743641701296.67041725 425621.14765075
#Sta/Elev= 30
       0  1095.5    15.2 1087.68    44.1 1070.88    56.5 1066.97    81.3 1062.36
    96.4 1057.03   118.4 1056.13   143.2 1056.81   152.8 1055.56  161.181052.067
   168.5 1050.91   174.2 1052.02   179.9 1055.05     183 1055.65   195.8 1054.72
   250.4 1055.81   279.2 1057.47   311.3 1061.73   330.5 1060.91   356.2  1061.4
     359 1062.03   367.4 1066.42   384.1 1067.91   392.5 1071.39   413.4 1077.93
   421.7  1083.1   442.4 1088.64   459.4 1096.53   484.6 1111.73   514.3 1127.89
#Mann= 8 ,-1,0
       0      .1       0     120     .05       0  156.44      .1       0
  161.18    .045       0   174.2      .1       0  220.79     .05       0
  330.79     .08       0  430.79      .1       0
Bank Sta=161.18,174.2
XS Rating Curve= 0 ,0
Exp/Cntr(USF)=0,0
Exp/Cntr=0.3,0.1

Type RM Length L Ch R = 1 ,3098    ,39.4,39.4,39.1
BEGIN DESCRIPTION:
Structure 4 XS 3
END DESCRIPTION:
XS GIS Cut Line= 3
1700719.94782658425530.9065625931701134.38649996425653.233367312
1701227.36216655425738.916824754
#Sta/Elev= 30
       0 1138.64    20.8 1132.06    25.2 1130.01    36.9 1121.98    46.5 1113.89
    71.1 1095.33    91.9 1085.73   108.6 1074.26     117 1069.54   129.5 1064.44
   154.5 1058.09   162.8 1054.92   178.6 1052.85   183.7 1051.11     192 1050.05
   200.4 1051.19   207.5 1053.98   212.9 1054.61   304.6 1055.19   371.4 1059.88
   404.7 1061.01   420.1 1060.53   435.7 1067.93     447 1072.46   466.5 1084.12
   486.6 1094.62   510.6 1108.99   540.4 1125.48   548.9 1129.12   558.6 1131.77
#Mann= 6 ,-1,0
       0      .1       0   183.7    .045       0   200.4      .1       0
     310     .07       0     420     .06       0  512.11      .1       0
Bank Sta=183.7,200.4
XS Rating Curve= 0 ,0
Exp/Cntr(USF)=0,0
Exp/Cntr=0.3,0.1

Type RM Length L Ch R = 1 ,3059    ,197,199.5,201.4
BEGIN DESCRIPTION:
Structure 4 XS 2
END DESCRIPTION:
XS GIS Cut Line= 3
 1700709.2829707425566.1826243271701118.73489824425685.857278012
 1701208.9759864 425764.24852631
#Sta/Elev= 30
       0 1139.09    13.9 1135.15    23.8 1129.99    36.3 1121.24    48.8 1110.83
    69.6 1096.23    82.1 1090.71    94.5  1083.7   129.9 1059.31   140.5 1056.05
   161.3 1054.61  168.871051.278   175.1 1049.64   181.5    1050   186.3 1051.32
   191.2    1053   197.7 1053.85   250.8 1053.35   348.8 1057.54   371.7 1057.83
     403 1061.06   419.7 1060.56   423.9  1062.1   433.7 1071.31     449 1082.01
   479.5 1095.67     489 1102.95     523 1124.52   534.4 1129.72   546.1 1132.68
#Mann= 6 ,-1,0
       0      .1       0  168.87    .045       0   186.3      .1       0
     320     .07       0  426.58     .06       0  456.58      .1       0
Bank Sta=168.87,186.3
XS Rating Curve= 0 ,0
Exp/Cntr(USF)=0,0
Exp/Cntr=0.3,0.1

Type RM Length L Ch R = 1 ,2859    ,356.6,358,359.1
BEGIN DESCRIPTION:
Structure 4 XS 1
END DESCRIPTION:
XS GIS Cut Line= 6
1700598.68487181425690.649093566 1700742.6967229425765.927486328
 1700831.3185929 425812.254165321700899.16524199425844.993601156
1700979.39769307425883.6319753211701065.08682615425926.469159989
#Sta/Elev= 30
       0 1165.49     6.1 1161.71    15.2 1154.28    24.2 1149.39    87.5 1131.92
   109.9 1129.31   116.3 1127.33     125 1123.31   132.5 1117.76   159.6 1093.94
   177.6 1083.84   191.2 1070.41   200.2 1062.77   213.7 1052.07   218.3 1050.02
   230.7 1048.29   236.3 1048.72  240.181050.111   245.3 1051.71     290    1052
   352.2 1054.98     370 1055.07   419.1 1060.01   441.1 1059.89   445.6 1063.08
   451.9 1069.18   463.9 1076.26   481.3 1089.45   500.5  1102.5   522.7 1120.67
#Mann= 7 ,-1,0
       0      .1       0   218.3    .045       0  240.18      .1       0
   252.5     .06       0  367.83     .07       0  466.88     .06       0
  476.88      .1       0
Bank Sta=218.3,240.18
XS Rating Curve= 0 ,0
Exp/Cntr(USF)=0,0
Exp/Cntr=0.3,0.1

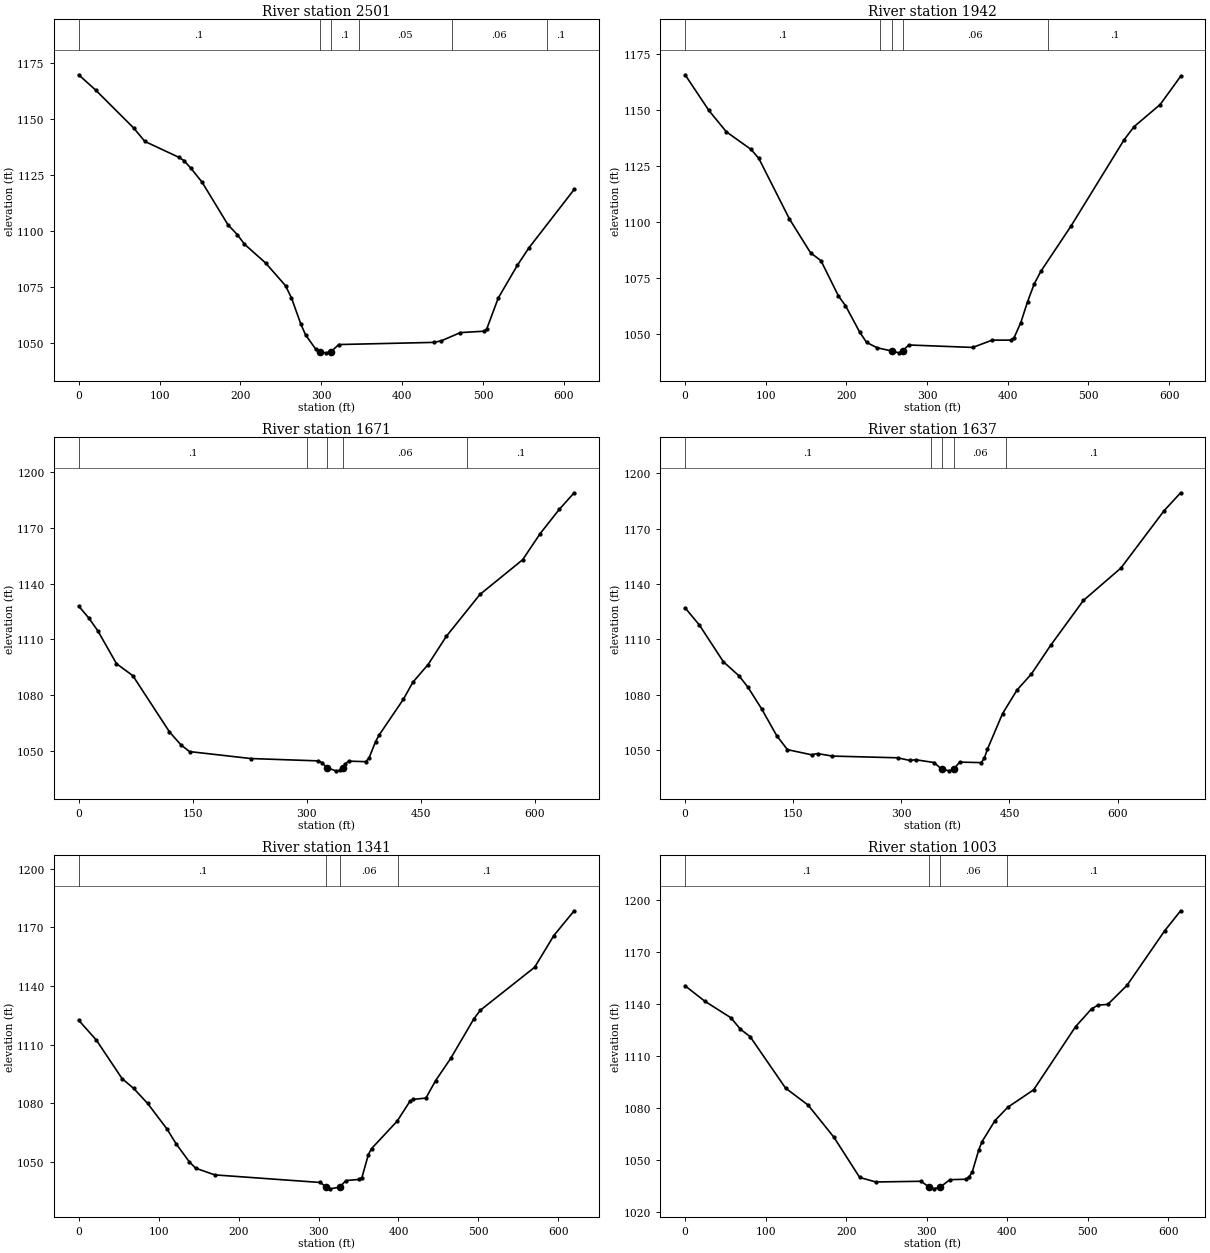
Type RM Length L Ch R = 1 ,2501    ,560.5,559.6,558.6
XS GIS Cut Line= 6
1700334.32820167425924.4289609191700414.17121784425973.563377082
1700637.73146626426111.1392174211700701.60568234 426150.44622542
1700776.12554643426196.3050575851700855.96823451426245.439801842
#Sta/Elev= 30
       0 1169.78    20.9    1163    67.9 1146.05    81.9 1139.99   124.2 1132.85
     130 1131.47   138.3 1128.22   152.6 1121.78   184.5 1102.79   196.2 1098.33
   204.9  1094.1   231.1 1085.68   255.7 1075.53   263.1 1070.04   274.5 1058.52
   280.5 1053.54   293.3 1047.05   298.2 1045.89   305.5 1045.52  311.611045.908
   321.5 1049.23   438.9 1050.19   448.3 1050.89   471.8 1054.57   501.5 1055.19
   504.4 1056.17   518.7 1070.03   542.4  1084.7   556.3  1092.3   612.5 1118.54
#Mann= 6 ,-1,0
       0      .1       0   298.2    .045       0  311.61      .1       0
  346.25     .05       0  461.25     .06       0  578.75      .1       0
Bank Sta=298.2,311.61
XS Rating Curve= 0 ,0
Exp/Cntr(USF)=0,0
Exp/Cntr=0.3,0.1

Type RM Length L Ch R = 1 ,1942    ,263.9,270.4,270.8
BEGIN DESCRIPTION:
Structure 3 XS 4
END DESCRIPTION:
XS GIS Cut Line= 6
1700108.01630073 426486.396749441700195.36848823 426520.57876769
1700276.03761824426554.479618522 1700436.7918899426623.639913264
1700486.18131376 426644.96840911 1700684.0098994426695.494100261
#Sta/Elev= 30
       0 1165.55    29.5 1149.64    51.1 1140.15    81.7  1132.3    91.3 1128.34
   129.3 1101.33   155.6 1086.19   168.4 1082.73   190.1    1067   198.8 1062.69
   216.2 1051.05   224.9 1046.31     238 1043.92   256.3 1042.46   265.1 1041.65
  269.521042.462   277.2 1045.15   356.5 1044.06   380.8 1047.32   403.5 1047.31
   407.9 1048.46   416.2 1055.16   424.5 1064.41   432.7 1072.28   440.9 1077.92
   478.2 1098.03   544.2 1136.57   556.6 1142.45   588.9 1152.28   614.3 1164.87
#Mann= 5 ,-1,0
       0      .1       0  241.31     .07       0   256.3    .045       0
  269.52     .06       0   450.1      .1       0
Bank Sta=256.3,269.52
XS Rating Curve= 0 ,0
Exp/Cntr(USF)=0,0
Exp/Cntr=0.3,0.1

Type RM Length L Ch R = 1 ,1671    ,35.6,34.5,33.9
BEGIN DESCRIPTION:
Structure 3 XS 3
END DESCRIPTION:
XS GIS Cut Line= 6
1700095.29542661426623.3537668451700192.82872392426732.736904005
1700259.37013235426765.5518451531700344.14206365426817.508835304
1700417.97568124426851.2353025941700667.73384442426868.554299311
#Sta/Elev= 30
       0 1127.89    13.3  1121.5    25.3  1114.5    49.8 1096.83    71.3 1090.36
   119.5 1060.05   134.6 1053.06   145.9 1049.45   226.5 1045.71   315.4 1044.44
   320.1  1043.5  326.12 1040.84   338.3 1039.08   343.6 1039.27  347.69 1040.81
   350.9 1042.93   355.3 1044.31   377.3 1044.02   381.7 1045.76   390.5 1054.83
   394.9 1058.19   427.1 1077.67   439.6 1086.85   459.6 1096.38   483.7 1111.65
   527.8 1134.16   583.9 1152.83     607 1166.95     632 1179.95   651.7 1188.94
#Mann= 5 ,-1,0
       0      .1       0  300.74     .06       0  326.12    .045       0
  347.69     .06       0  511.34      .1       0
Bank Sta=326.12,347.69
XS Rating Curve= 0 ,0
Exp/Cntr(USF)=0,0
Exp/Cntr=0.3,0.1

Type RM Length L Ch R = 1 ,1637    ,298,295.9,292.7
BEGIN DESCRIPTION:
Structure 3 XS 2
END DESCRIPTION:
XS GIS Cut Line= 6
 1700071.5957469426634.2920805611700178.24430563426765.551845153
1700289.45049507426813.8627307321700339.54108987426854.048162889
1700415.24110281426882.1838483881700666.82231827426894.988557458
#Sta/Elev= 30
       0 1127.08    19.9 1117.76    53.1 1097.91      75 1090.21    87.3 1084.06
     106 1072.52   127.1 1057.91     142 1050.33   175.4 1047.56   183.9  1048.2
   204.1 1046.85   294.8 1045.92   311.4 1044.52   320.4 1044.84   345.3 1043.36
  356.131039.728   366.5 1038.86   372.5 1039.76     381 1043.59   410.9 1043.31
   415.1 1045.68   419.4 1050.53   440.4 1069.83   460.5 1082.61   480.5 1091.31
   507.2 1106.83   552.6  1131.1   604.6 1148.61   664.7 1179.75   687.5 1189.38
#Mann= 5 ,-1,0
       0      .1       0  340.58     .06       0  356.13    .045       0
   372.5     .06       0  445.55      .1       0
Bank Sta=356.13,372.5
XS Rating Curve= 0 ,0
Exp/Cntr(USF)=0,0
Exp/Cntr=0.3,0.1

Type RM Length L Ch R = 1 ,1341    ,337.1,337.5,337.2
BEGIN DESCRIPTION:
Structure 3 XS 1
END DESCRIPTION:
XS GIS Cut Line= 2
1700025.77083164427150.2047908441700645.42850715427149.426772422
#Sta/Elev= 30
       0 1122.46    22.3  1112.2    54.3 1092.56    68.8 1087.55    86.3 1079.83
   110.3 1066.86   122.3 1058.95   138.3 1050.01   146.3 1046.69   170.3 1043.26
   302.3 1039.37  309.571037.048   314.3 1036.12   326.3 1036.95   334.3 1040.36
   350.3 1040.92   354.3  1041.9   362.3 1053.62   366.3 1056.72   398.3 1070.76
   414.3 1080.93   418.3 1081.92   434.3 1082.58   446.3 1091.44   465.3  1102.9
   494.3 1123.16   502.3 1127.53   570.3 1149.56   594.3 1165.79   619.7 1178.46
#Mann= 4 ,-1,0
       0      .1       0  309.57    .045       0   326.3     .06       0
     400      .1       0
Bank Sta=309.57,326.3
XS Rating Curve= 0 ,0
Exp/Cntr(USF)=0,0
Exp/Cntr=0.3,0.1

Type RM Length L Ch R = 1 ,1003    ,147.1,144.7,145.1
BEGIN DESCRIPTION:
Structure 2 XS 4
END DESCRIPTION:
XS GIS Cut Line= 6
1700027.37212268427476.1086003331700121.99496493427478.926508084
1700210.48822625427482.2050448361700286.33518742427485.197821006
  1700386.514449427485.3119940011700642.53296584427474.420939669
#Sta/Elev= 30
       0 1150.31    24.8 1141.33    56.8 1131.93    68.8 1125.29    80.8 1121.01
   124.8 1091.37   152.8 1081.59   184.8 1063.11   216.9 1039.89   236.9 1037.28
   292.9 1037.69  303.551034.255   308.9 1033.33   316.9 1034.31   328.9 1038.61
   348.9 1038.86   352.9 1040.25   356.9 1043.29   364.9 1055.93   368.9 1060.53
   384.9 1072.63   400.9 1080.36     433 1090.39     485 1126.74     505 1137.05
     513 1139.18   525.1  1139.6   549.1 1150.65   595.8 1182.04   615.6 1193.54
#Mann= 4 ,-1,0
       0      .1       0  303.55    .045       0   316.9     .06       0
   399.3      .1       0
Bank Sta=303.55,316.9
XS Rating Curve= 0 ,0
Exp/Cntr(USF)=0,0
Exp/Cntr=0.3,0.1