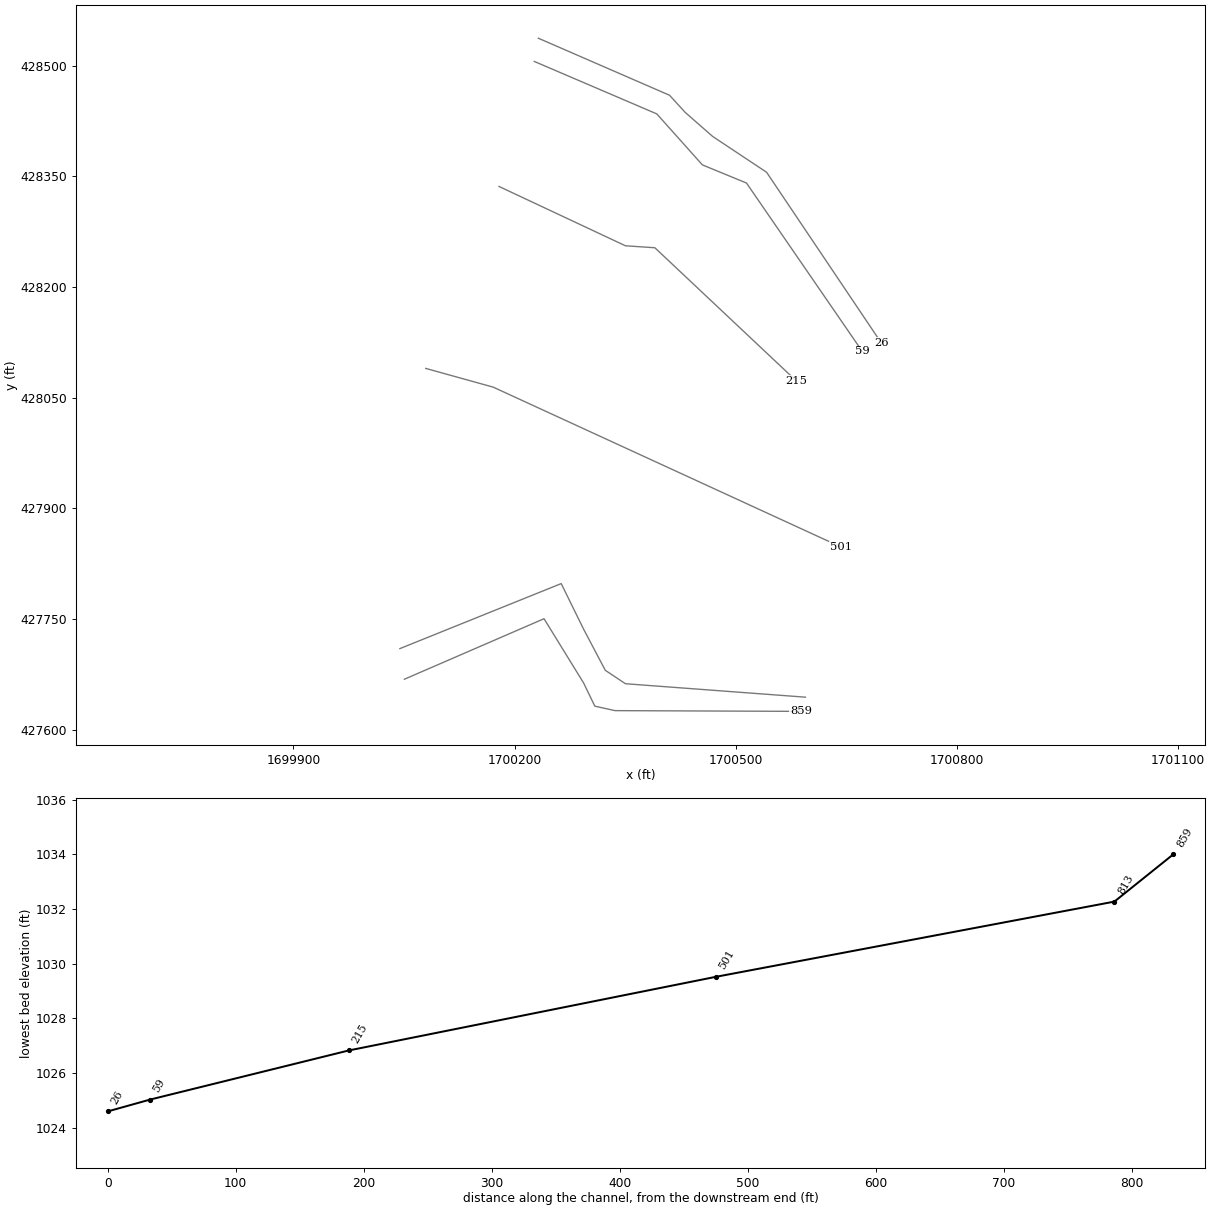
HEC-RAS study RUSHRN2.prj: RUSHRN2

--- RUSHRN2.g01 (geometry) --- (continued)

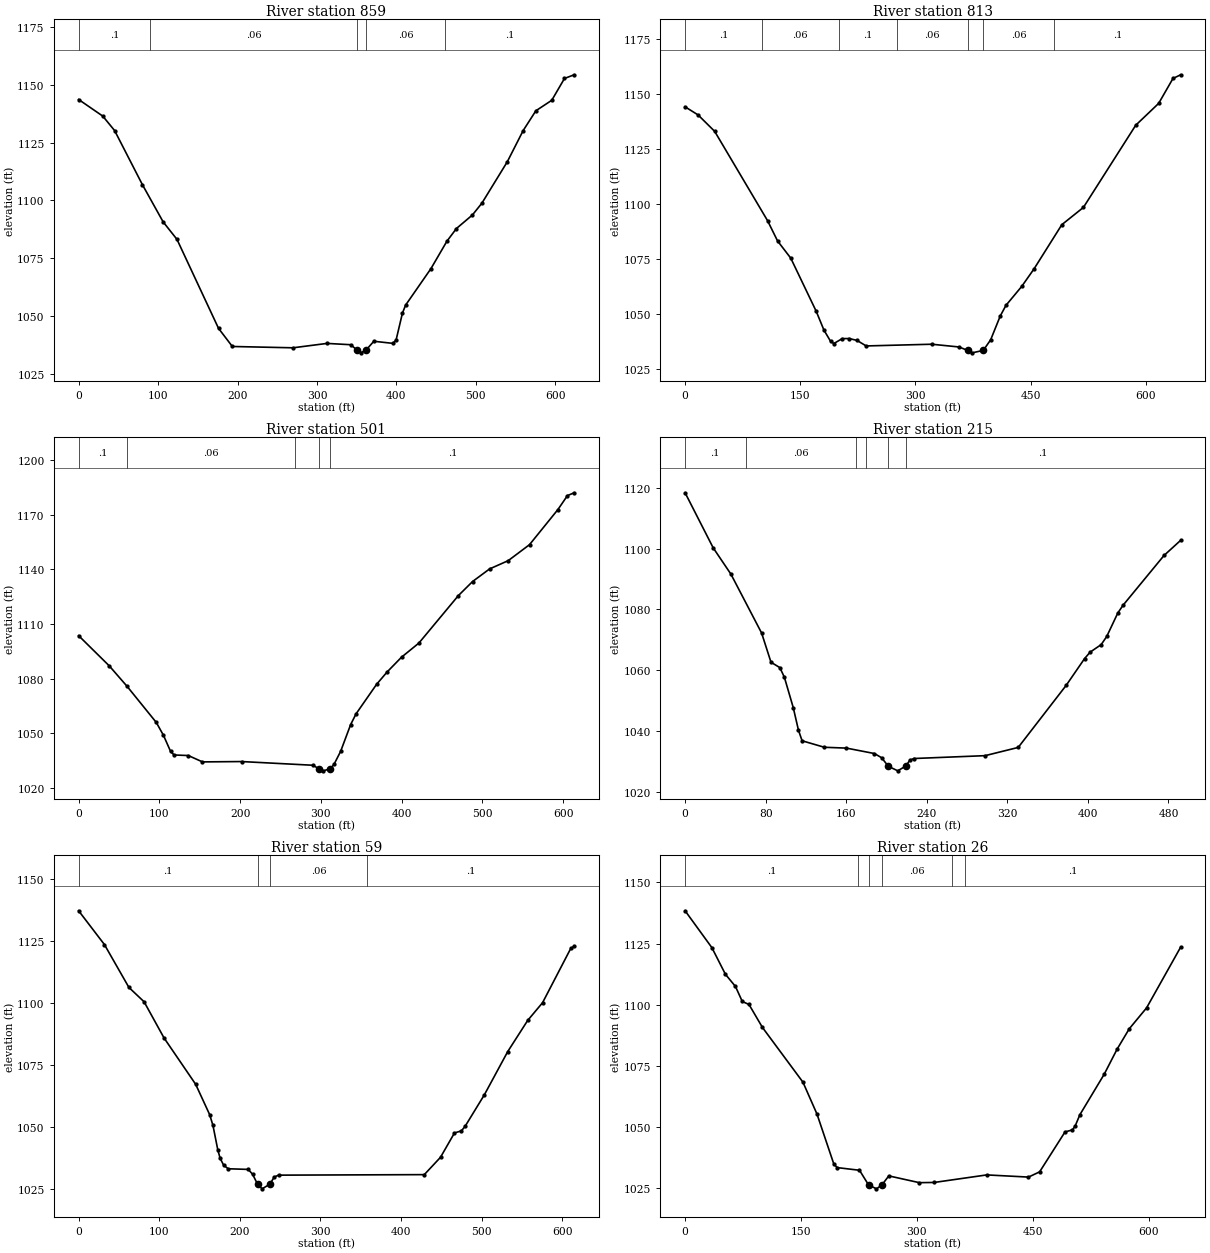
Type RM Length L Ch R = 1 ,859     ,51.3,46.1,43.9
BEGIN DESCRIPTION:
Structure 2 XS 3
END DESCRIPTION:
XS GIS Cut Line= 6
1700050.52516116427668.4474973951700239.92003754427750.484850265
 1700293.5987993427663.3834632671700308.79090168427631.986451675
1700336.13668597427625.9096107221700588.32558553427624.896803897
#Sta/Elev= 30
       0 1143.64    30.4 1136.45    45.3 1130.19    80.2 1106.83   106.4 1090.66
   123.8 1083.11   176.1  1044.6   193.5 1036.75   269.8 1036.18   312.7 1038.08
   342.7 1037.51  350.27 1035.21   355.2    1034  361.86 1035.21   371.6 1039.01
   395.6  1038.1   399.6 1039.51   407.6 1051.18   411.6 1054.65   443.6  1070.5
   463.6 1082.31   475.6 1087.81   495.6 1093.63   507.6 1098.75   539.6 1116.68
   559.6  1130.2   575.6 1138.77   595.6  1143.3   611.6 1152.75   623.8 1154.34
#Mann= 5 ,-1,0
       0      .1       0      90     .06       0  350.27    .045       0
  361.86     .06       0   461.6      .1       0
Bank Sta=350.27,361.86
XS Rating Curve= 0 ,0
Exp/Cntr(USF)=0,0
Exp/Cntr=0.3,0.1

Type RM Length L Ch R = 1 ,813     ,307.6,311.4,312.8
BEGIN DESCRIPTION:
Structure 2 XS 2
END DESCRIPTION:
XS GIS Cut Line= 6
1700044.44832021427709.9725772431700263.21459453427798.086771066
 1700293.5987993427736.3055547071700322.97019724427680.601179302
1700350.31598153427662.3706564421700594.40242649427644.140133582
#Sta/Elev= 30
       0 1144.27    16.9 1140.58    38.5 1133.11   107.4 1092.43   120.4 1083.21
   137.6 1075.38   170.8 1051.14   180.8 1042.62   189.4 1037.54   193.7 1036.51
   204.6 1038.74   213.8 1038.78   223.9 1037.92   235.8 1035.41   321.2 1036.19
   356.7 1034.94  367.951033.376   373.8 1032.27   388.3 1033.38   397.9  1038.2
   410.4 1049.04   417.8 1053.87   438.4 1062.53   454.5 1070.55   490.6 1090.62
   518.7 1098.48   586.8 1135.88   616.7 1145.84   635.3 1157.17   645.3 1158.86
#Mann= 7 ,-1,0
       0      .1       0     100     .06       0     200      .1       0
  275.84     .06       0  367.95    .045       0   388.3     .06       0
  480.53      .1       0
Bank Sta=367.95,388.3
XS Rating Curve= 0 ,0
Exp/Cntr(USF)=0,0
Exp/Cntr=0.3,0.1

Type RM Length L Ch R = 1 ,501     ,282.9,286.6,287.9
BEGIN DESCRIPTION:
Structure 2 XS 1
END DESCRIPTION:
XS GIS Cut Line= 6
  1700079.522937428089.7458245011700171.02931568428064.356111512
1700250.53867109428027.8246885091700409.55705383427954.762498677
1700477.70816426427923.4502253381700642.40599759427847.778460667
#Sta/Elev= 30
       0 1103.61      38 1087.03      60 1075.84    96.2 1056.03     105 1049.04
   113.8 1040.25   118.2 1038.21   135.8 1037.91   153.4 1034.42   201.8 1034.61
   289.8 1032.59   297.7 1030.71   303.1 1029.52   311.9 1030.73   316.3 1033.08
   324.5 1040.22   336.9  1054.9   343.6 1060.78   369.1    1077   382.2 1083.79
   399.9 1091.82   421.4 1099.56   470.3 1125.59   487.9  1133.3   508.9 1140.19
     532 1144.73   558.4  1153.5   593.6 1172.77   605.4 1180.41   613.7 1181.94
#Mann= 5 ,-1,0
       0      .1       0      60     .06       0  267.46      .1       0
   297.7    .045       0   311.9      .1       0
Bank Sta=297.7,311.9
XS Rating Curve= 0 ,0
Exp/Cntr(USF)=0,0
Exp/Cntr=0.3,0.1

Type RM Length L Ch R = 1 ,215     ,162.7,155.6,150.3
BEGIN DESCRIPTION:
Structure 1 XS 4
END DESCRIPTION:
XS GIS Cut Line= 4
1700178.88756461428336.3553104341700350.32922464428255.950500887
1700390.19937813428253.2924906541700581.57611491 428073.21229737
#Sta/Elev= 30
       0 1118.42    27.9 1100.28    45.5 1091.62      76 1072.21    85.3  1062.6
    94.1 1060.83    98.6 1057.65   107.4 1047.66   112.6 1040.19   116.2 1036.73
   138.3 1034.59   160.2 1034.32     188 1032.53   195.2 1031.14   201.8 1028.34
   211.2 1026.83   219.2 1028.43   223.2 1030.33   227.2 1030.89   297.9 1031.83
   330.8 1034.54   378.4 1054.97   396.7  1063.8   402.2 1065.92   413.2 1068.41
   418.7 1071.08   429.7 1078.81   434.9 1081.37   475.6 1097.77   492.1 1102.75
#Mann= 6 ,-1,0
       0      .1       0      60     .06       0     170     .05       0
     180      .1       0   201.8    .045       0   219.2      .1       0
Bank Sta=201.8,219.2
XS Rating Curve= 0 ,0
Exp/Cntr(USF)=0,0
Exp/Cntr=0.3,0.1

Type RM Length L Ch R = 1 ,59      ,31.9,32.9,33.8
BEGIN DESCRIPTION:
Structure 1 XS 3
END DESCRIPTION:
XS GIS Cut Line= 5
 1700226.7317488428505.8034627861700392.85738837428434.701689054
1700454.65612628428365.5934229971700514.46135652428341.006828342
1700671.28396027428113.082450864
#Sta/Elev= 30
       0 1137.36      32 1123.71    62.4 1106.38    81.2  1100.6   105.9 1086.01
   145.2 1067.25   162.5 1055.03   166.6 1050.69   172.6 1040.82   175.5  1037.4
   179.9 1034.57   185.6 1033.14   210.4 1032.88   215.8 1030.92  221.881026.942
   227.6 1025.03   237.3 1026.94   242.6  1029.8     248 1030.56   428.8 1030.77
   448.9 1037.78   466.2  1047.6   474.8 1048.46   479.4 1050.28   503.3 1063.02
   532.3 1080.49   557.1 1093.09   575.5 1100.23   610.5 1122.17   614.7 1122.98
#Mann= 4 ,-1,0
       0      .1       0  221.88    .045       0   237.3     .06       0
  358.07      .1       0
Bank Sta=221.88,237.3
XS Rating Curve= 0 ,0
Exp/Cntr(USF)=0,0
Exp/Cntr=0.3,0.1

Type RM Length L Ch R = 1 ,26      ,,,
BEGIN DESCRIPTION:
Structure 1 XS 2
END DESCRIPTION:
XS GIS Cut Line= 6
1700232.27352391428537.2520262461700410.13445488428459.952786268
1700431.39853674428436.6951967291700468.61068001428404.134571375
1700541.70596141428355.6258846231700697.19956004428124.378994355
#Sta/Elev= 30
       0  1138.4    34.7 1123.29    52.2  1112.4    65.2 1107.42      74 1101.28
    82.7 1100.05   100.1 1090.65   152.5 1068.26   170.7 1055.19   192.5 1034.73
   196.9 1033.29   225.7  1032.2   237.4 1026.22   247.7  1024.6  254.87 1026.25
   263.6  1029.9   303.1 1027.13   322.3 1027.21   390.4  1030.3   444.4 1029.41
   458.8 1031.55   491.7  1047.9   501.3 1048.72   504.9 1050.38   510.9 1054.93
   542.4 1071.51   559.1 1081.78   574.8  1090.1   597.2 1098.65   641.3 1123.51
#Mann= 6 ,-1,0
       0      .1       0  223.93     .06       0   237.4    .045       0
  254.87     .06       0  344.89     .05       0  362.62      .1       0
Bank Sta=237.4,254.87
XS Rating Curve= 0 ,0
Exp/Cntr(USF)=0,0
Exp/Cntr=0.3,0.1
LCMann Table=0

Chan Stop Cuts=-1
Use User Specified Reach Order=0
Composite Channel Slope=5